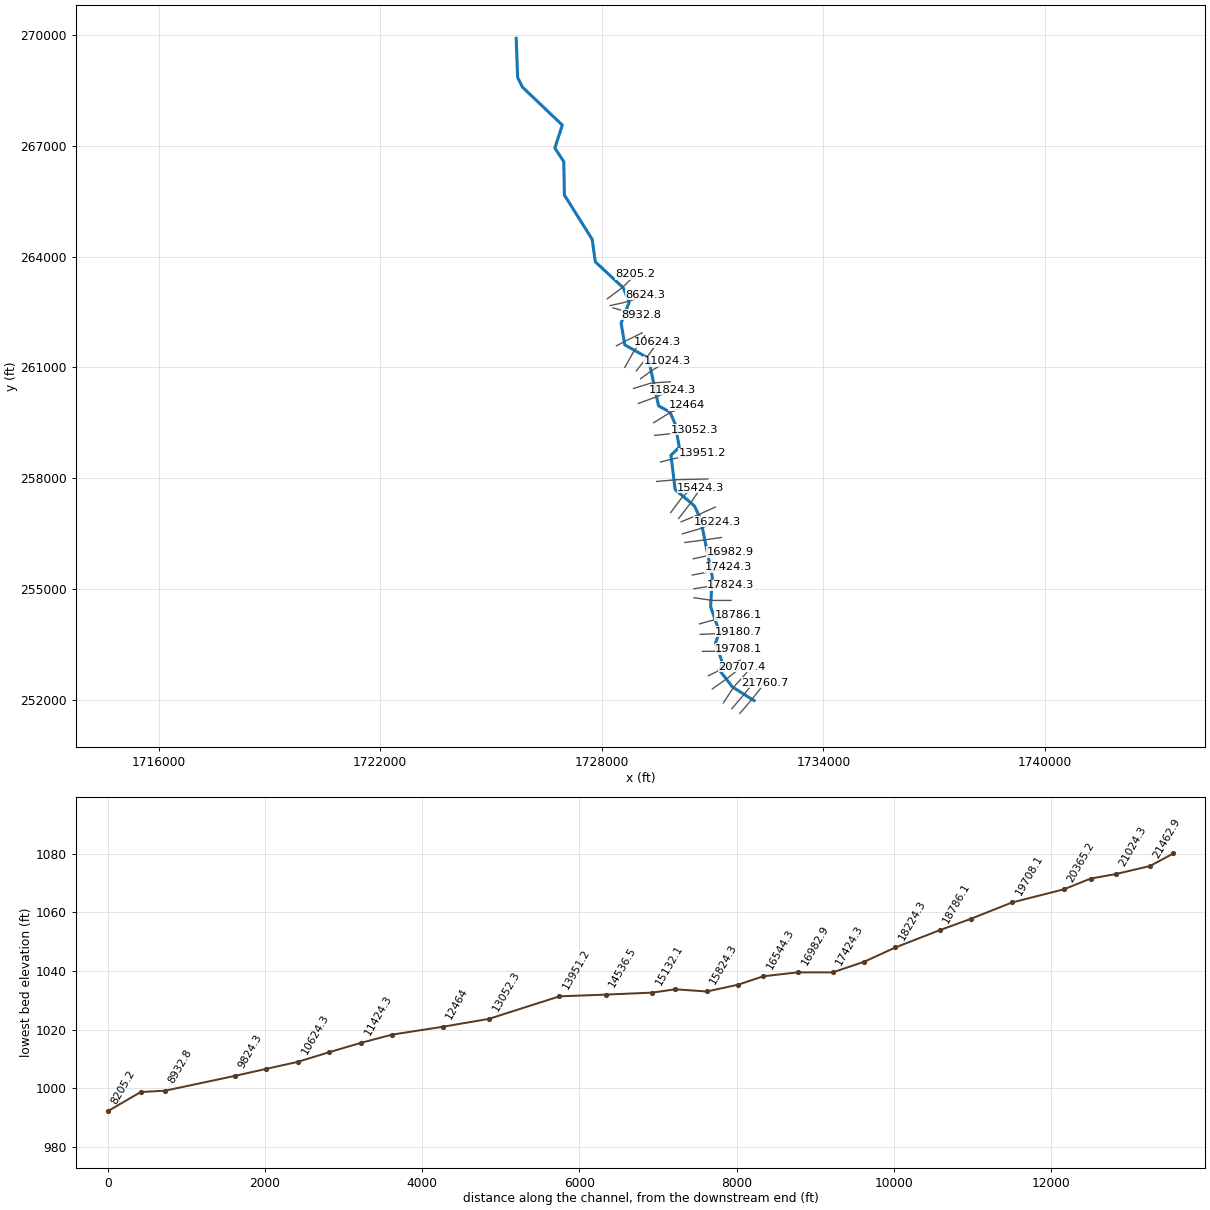
--- BrownsCr.prj (project) ---

Proj Title=BrownsCr
Current Plan=p01
Default Exp/Contr=0,0
English Units
Geom File=g01
Flow File=f01
Plan File=p01
BEGIN DESCRIPTION:
END DESCRIPTION:
DSS Export Rating Curves= 0
DSS Export Rating Curve Sorted= 0
DSS Export Volume Flow Curves= 0
DXF OffsetX= 0
DXF OffsetY= 0
DXF ScaleX= 0
DXF ScaleY= 0

--- BrownsCr.p01 (plan) ---

Plan Title=Floodplain
Program Version=4.00
Geom File=g01
Flow File=f01
K Sum by GR=0
Std Step Tol=0.01
Critical Tol=0.01
Num of Std Step Trials=20
Max Error Tol=0.3
Flow Tol Ratio=0.001
Split Flow NTrial=30
Split Flow Tol=0.02
Split Flow Ratio=0.02
Log Output Level=0
Friction Slope Method=1
Unsteady Friction Slope Method=2
Unsteady Bridges Friction Slope Method=1
Global Log Level=0
CheckData=False
Run HTab=0
Run UNet=0
Run PostProcess=0
UNET Theta=0
UNET Theta Warmup=0
UNET ZTol=0
UNET ZSATol=0
UNET MxIter=0
UNET MaxInSteps=0
UNET DtIC=0
UNET DtMin=0
UNET MaxCRTS=0
UNET WFStab=0
UNET SFStab=0
UNET WFX=0
UNET SFX=0
UNET DSS MLevel=0
UNET DZMax Abort=0
UNET Convert EG Bridges=0
UNET Use Existing IB Tables=0
UNET Froude Limit=0
UNET Froude Power=0
Write IC File=0
Echo Input=False
Echo Output=False
Write Detailed=0

--- BrownsCr.f01 (steady flow) ---

Flow Title=NFF Regression Equation
Program Version=4.00
Number of Profiles=1
Profile Names=P100yr
River Rch & RM=BrownsCr,Main      ,21760.7
613.3953
River Rch & RM=BrownsCr,Main      ,21462.9
613.3953
River Rch & RM=BrownsCr,Main      ,21024.3
739.0180
River Rch & RM=BrownsCr,Main      ,20365.2
755.7722
River Rch & RM=BrownsCr,Main      ,18224.3
836.0263
River Rch & RM=BrownsCr,Main      ,18224.3
925.8749
River Rch & RM=BrownsCr,Main      ,16544.3
947.4134
River Rch & RM=BrownsCr,Main      ,16544.3
1050.478
River Rch & RM=BrownsCr,Main      ,13052.3
1165.694
River Rch & RM=BrownsCr,Main      ,12464
1330.911
River Rch & RM=BrownsCr,Main      ,11424.3
1378.334
River Rch & RM=BrownsCr,Main      ,10224.3
1522.123
River Rch & RM=BrownsCr,Main      ,8932.8
1552.822
River Rch & RM=BrownsCr,Main      ,8624.3
1702.913
River Rch & RM=BrownsCr,Main      ,6161.2
1875.897
River Rch & RM=BrownsCr,Main      ,3017.4
2028.028
River Rch & RM=BrownsCr,Main      ,224.3
2212.866
Boundary for River Rch & Prof#=BrownsCr,Main      ,1
Up Type=0
Dn Type=3
Dn Slope=0.00714

--- BrownsCr.g01 (geometry) ---

Geom Title=USGS 3m DEM
Program Version=4.00

River Reach=BrownsCr        ,Main
Reach XY= 30
     1732126.079      251975.162     1731538.924      252343.214
     1731175.716      252814.944     1731273.502      252973.833
     1731080.537      253543.429     1731188.804       253825.07
     1730947.407      254522.088      1730993.63      255316.925
     1730675.375      256900.163     1730506.292      257249.889
     1729986.575      257690.383     1729874.124      258619.703
     1730099.075      258837.527     1729982.916       259476.57
     1729845.252      259789.049     1729538.261      259957.638
     1729261.367      261249.395     1728623.152      261608.488
     1728524.545      262199.201     1728741.579      262756.571
     1728582.003      263153.379     1727825.577       263856.97
     1727739.911      264468.256     1726987.739      265665.423
     1726971.094      266570.433     1726730.138      266938.534
     1726931.435      267560.255     1725855.339      268585.109
     1725722.512      268844.781     1725682.958      269908.984

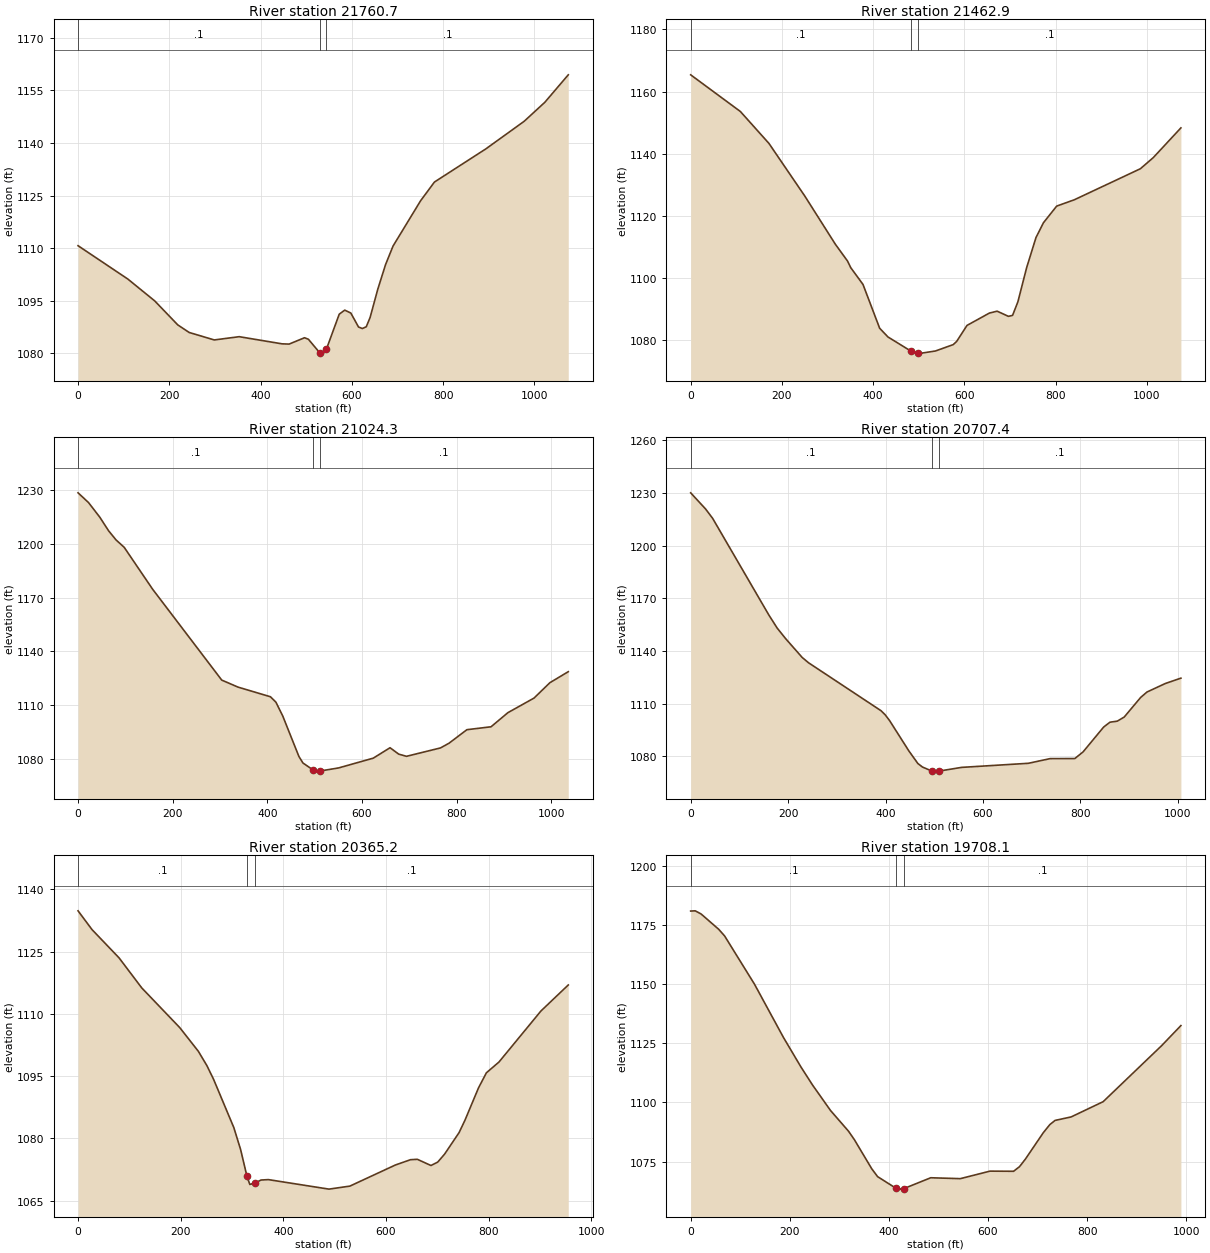
Type RM Length L Ch R = 1 ,21760.7 ,298.918,297.797,297.667
XS GIS Cut Line= 3
     1731739.455      251629.298     1732056.141      251997.943
     1732420.526      252459.931
#Sta/Elev= 30
       0 1110.68   109.1 1101.17     168 1094.94   218.5  1088.1   243.6 1085.93
   298.6  1083.8   353.2 1084.73   447.1 1082.69   462.6 1082.62   496.4 1084.43
   504.9 1083.99   529.4 1080.19   538.1 1080.04   544.4  1081.2   572.5 1091.16
   584.5  1092.3   597.8 1091.48   614.7 1087.49   623.2 1087.06   631.7 1087.56
   640.1 1090.22     657  1098.3   673.9 1105.27   690.4 1110.59   750.8 1123.51
   781.1 1128.84   893.7 1138.29   977.7 1146.16    1023 1151.58  1074.4 1159.42
#Mann= 3 , 0 , 0
       0      .1       0   529.4    .045       0   544.4      .1       0
#XS Ineff= 2 , 0
          496.37 1084.42
Permanent Ineff=
       F       F
Bank Sta=529.4,544.4
XS Rating Curve= 0 ,0
Exp/Cntr=0.3,0.1

Type RM Length L Ch R = 1 ,21462.9 ,405.886,438.596,436.35
XS GIS Cut Line= 3
     1731521.754      251755.264      1731838.44      252123.908
     1732202.825      252585.896
#Sta/Elev= 30
       0 1165.38   108.9 1153.57   171.5 1143.29   250.1 1126.33   317.2 1110.78
   343.6 1105.43   350.9 1103.24   377.6 1097.87   414.1 1083.76   432.3 1080.95
   482.9 1076.37   497.9 1075.83   506.2 1075.74   536.4 1076.43   575.3 1078.48
   582.9 1079.51   605.5 1084.66   654.7 1088.65   671.6 1089.25   696.3 1087.59
   705.4  1087.9   717.1 1092.29   736.2 1103.25   756.7 1112.96   773.1 1117.74
   802.1  1123.1   840.7 1125.13   985.5 1135.13  1013.8 1138.72  1074.3 1148.29
#Mann= 3 , 0 , 0
       0      .1       0   482.9    .045       0   497.9      .1       0
Bank Sta=482.9,497.9
XS Rating Curve= 0 ,0
Exp/Cntr=0.3,0.1

Type RM Length L Ch R = 1 ,21024.3 ,326.72,316.877,309.228
XS GIS Cut Line= 3
      1731295.32      251914.291     1731569.223      252337.426
     1731924.268      252733.448
#Sta/Elev= 30
       0 1228.54    22.1 1223.11      46 1214.91    64.5 1207.35    80.3 1202.21
    97.5 1198.09   157.6 1174.66   303.6 1123.88   337.9 1119.96   406.6 1114.55
   418.1 1111.54   432.6 1103.78   466.7 1081.19   475.3 1077.52   496.5 1073.69
   502.9 1072.99   511.5 1073.06   550.6 1074.78   623.7 1080.23   659.3 1086.06
   677.7 1082.48   694.1 1081.27     766 1085.97   783.8 1088.57   821.7 1096.15
   872.7 1097.77   908.3 1105.66   963.5 1113.81   997.1 1122.42  1035.9 1128.57
#Mann= 3 , 0 , 0
       0      .1       0   496.5    .045       0   511.5      .1       0
Bank Sta=496.5,511.5
XS Rating Curve= 0 ,0
Exp/Cntr=0.3,0.1

Type RM Length L Ch R = 1 ,20707.4 ,345.688,342.267,324.343
XS GIS Cut Line= 3
     1730994.819      252292.298     1731402.479      252579.389
     1731798.403      252896.905
#Sta/Elev= 30
       0 1230.07    30.6 1220.85    45.1  1215.5   160.4 1160.45   177.5 1152.99
   194.5  1147.1   228.6 1136.31   241.7 1133.25   390.5 1105.92     399 1103.62
   408.2 1100.27   447.9 1082.93   466.3 1075.79   475.7 1073.78   494.4 1071.59
   508.9 1071.46   509.4 1071.47     556 1073.59     693 1075.92   737.7 1078.59
   788.4 1078.63   805.3 1082.42   847.5 1096.56   860.4 1099.33   875.6 1099.95
   889.8  1102.3   923.5 1113.45   936.5 1116.55   974.2 1121.41  1006.1 1124.45
#Mann= 3 , 0 , 0
       0      .1       0   494.4    .045       0   509.4      .1       0
Bank Sta=494.4,509.4
XS Rating Curve= 0 ,0
Exp/Cntr=0.3,0.1

Type RM Length L Ch R = 1 ,20365.2 ,668.502,657.102,661.944
XS GIS Cut Line= 3
     1730888.436      252650.965     1731187.752      252794.116
     1731747.344      253070.658
#Sta/Elev= 30
       0 1134.81    27.2 1130.29    79.9 1123.48   124.2 1116.23   198.3 1106.66
   234.3 1100.99     251 1097.53   264.1 1094.21   303.6 1082.56   316.7 1077.31
   328.9 1070.95   334.6 1068.91   343.9  1069.2   356.4 1069.97   370.8 1070.07
   488.8 1067.78   529.6 1068.51   618.2 1073.59   647.7 1074.87     661 1074.96
   687.5 1073.47   700.7 1074.29     714  1076.2   742.3  1081.4   753.7 1084.36
   780.2 1092.18   795.5  1095.8   819.9 1098.38   901.8 1110.69     955 1116.95
#Mann= 3 , 0 , 0
       0      .1       0   328.9    .045       0   343.9      .1       0
Bank Sta=328.9,343.9
XS Rating Curve= 0 ,0
Exp/Cntr=0.3,0.1

Type RM Length L Ch R = 1 ,19708.1 ,524.933,527.33,527.239
XS GIS Cut Line= 3
     1730725.764      253308.159     1731148.711      253311.413
     1731711.556      253373.228
#Sta/Elev= 30
       0 1180.95     9.1 1181.05      21 1179.72    56.6 1173.23    68.5 1170.41
   128.8    1150   187.2 1127.48   222.9 1114.86   245.7 1107.42   282.2 1096.58
   318.4 1087.85   330.4 1084.21   365.3 1071.95   377.2  1068.6     415 1063.59
   424.7 1063.32     430 1063.53   484.4 1068.13   544.1 1067.75   603.9 1070.93
   651.6 1070.87   663.6 1072.84   675.5 1076.05   711.4 1087.15   724.6 1090.59
   735.2 1092.38   767.7 1093.86   832.3 1100.31   950.2 1123.99   989.2  1132.5
#Mann= 3 , 0 , 0
       0      .1       0     415    .045       0     430      .1       0
Bank Sta=415,430
XS Rating Curve= 0 ,0
Exp/Cntr=0.3,0.1

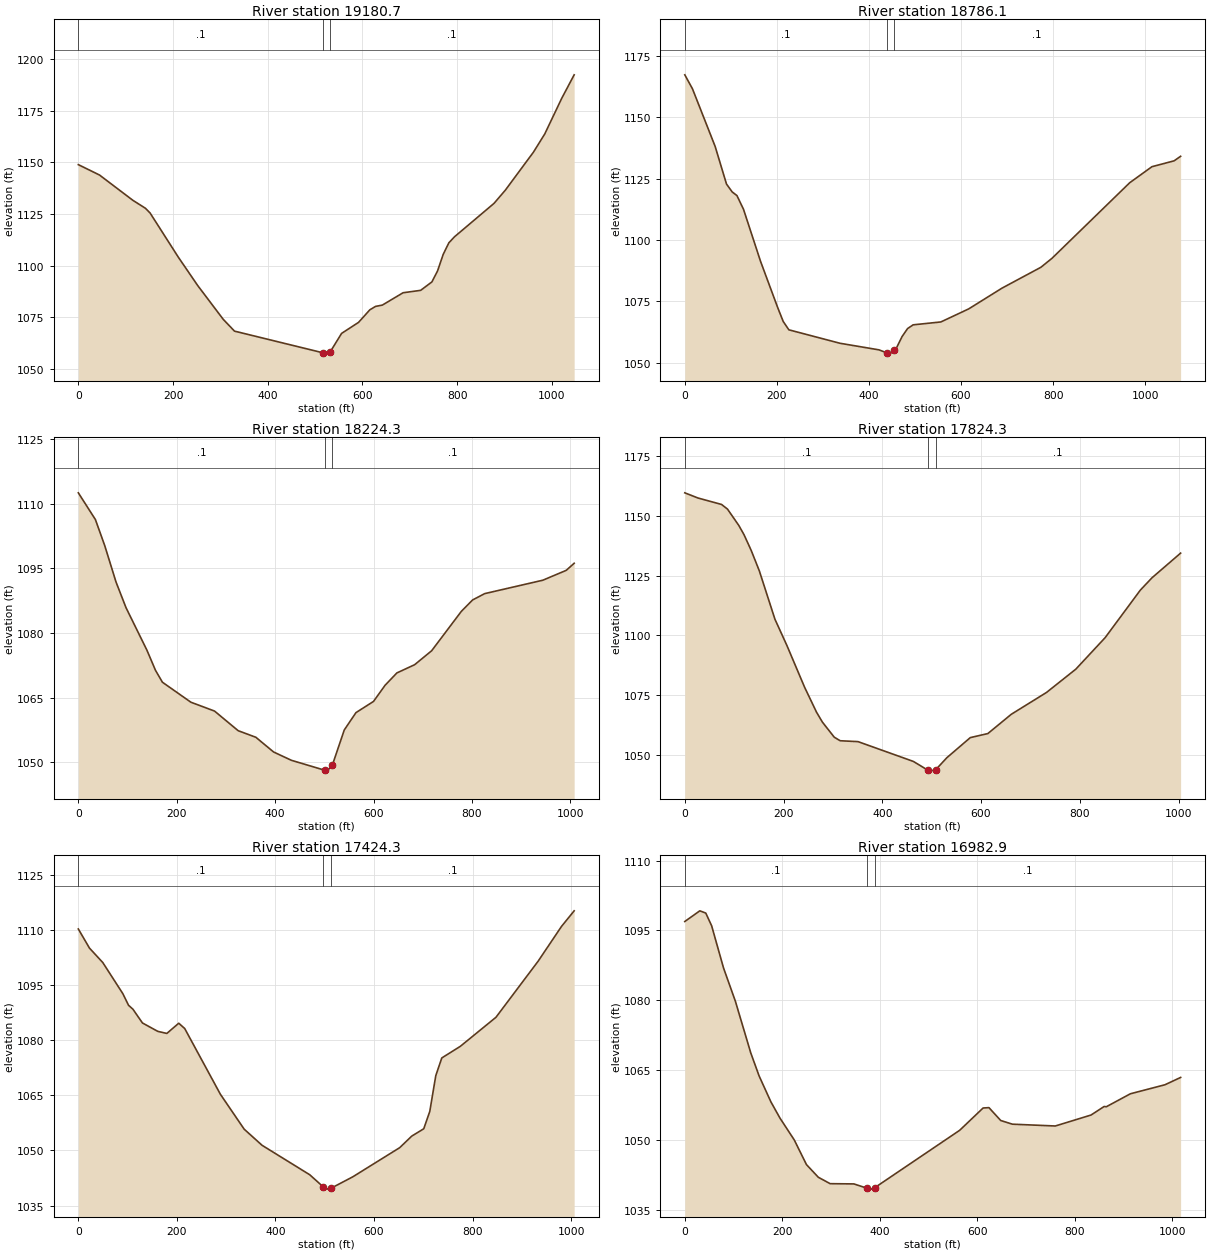
Type RM Length L Ch R = 1 ,19180.7 ,391.508,394.58,396.522
XS GIS Cut Line= 3
     1730666.525      253769.353     1731069.951       253785.62
     1731710.878      253840.929
#Sta/Elev= 30
       0 1148.88    44.7 1143.86   115.1 1131.64   141.7 1127.78   151.6 1125.47
     211 1104.18   252.1  1090.4   306.1 1074.03   329.8 1068.35   517.1 1057.84
   520.3 1057.71   532.1 1058.37     556 1067.26   591.8 1072.59   615.6 1078.65
   627.6  1080.3   642.1 1080.95   685.9 1086.92   722.9 1088.07   746.7 1092.16
   758.6 1097.47   770.6  1105.5   782.5 1111.07   794.4 1113.98   877.8 1130.13
   901.6 1136.48   961.2 1154.94   985.1 1163.76  1020.8 1180.93  1047.1 1192.32
#Mann= 3 , 0 , 0
       0      .1       0   517.1    .045       0   532.1      .1       0
Bank Sta=517.1,532.1
XS Rating Curve= 0 ,0
Exp/Cntr=0.3,0.1

Type RM Length L Ch R = 1 ,18786.1 ,570.41,561.844,557.555
XS GIS Cut Line= 3
     1730647.682      254053.196     1731067.375       254170.32
     1731698.542       254284.19
#Sta/Elev= 30
       0  1167.3    16.6 1161.63    65.9 1138.13    90.6 1122.78   102.9 1119.57
   113.3 1118.07   127.5  1112.5   164.5  1091.3   201.5 1072.58   213.8 1066.75
   226.1 1063.35   337.1 1057.87   421.6 1055.19     439 1053.97   441.2 1053.85
   447.8 1053.85     454 1055.04   459.8 1055.95   471.9 1060.57   483.9 1063.85
     496 1065.38   556.3 1066.56   616.7 1071.88     689 1080.33   773.5 1088.84
   797.6 1092.49   966.5 1123.31  1014.8 1129.85    1063 1132.24  1077.1 1134.09
#Mann= 3 , 0 , 0
       0      .1       0     439    .045       0     454      .1       0
Bank Sta=439,454
XS Rating Curve= 0 ,0
Exp/Cntr=0.3,0.1

Type RM Length L Ch R = 1 ,18224.3 ,393.015,400,400.966
XS GIS Cut Line= 3
     1730496.585      254761.377     1730999.765      254688.112
     1731498.855      254687.389
#Sta/Elev= 30
       0 1112.54    34.7 1106.34    53.8 1100.25    76.6 1091.85    96.9  1085.9
   139.4 1076.04   156.8 1071.37   170.9 1068.61   228.8 1063.97   276.8 1061.92
   324.8 1057.37   360.8 1055.84   396.8 1052.43     433  1050.5     501 1048.19
   504.8 1047.99     516  1049.3   540.4 1057.53   564.2 1061.56   599.8 1064.15
   623.5 1067.92   647.3 1070.76   683.5 1072.68     718 1075.91   778.3 1085.04
   801.2 1087.69   825.8 1089.16   943.9 1092.27   991.5 1094.56  1007.6  1096.2
#Mann= 3 , 0 , 0
       0      .1       0     501    .045       0     516      .1       0
Bank Sta=501,516
XS Rating Curve= 0 ,0
Exp/Cntr=0.3,0.1

Type RM Length L Ch R = 1 ,17824.3 ,399.6,400,404.347
XS GIS Cut Line= 3
     1730495.127      255004.163     1730989.566      255080.928
     1731493.122      255097.051
#Sta/Elev= 30
       0 1159.76    26.8 1157.58    74.4 1154.89    86.5 1152.93   109.3 1146.11
   119.7  1142.3   134.5 1135.61   150.9 1127.07   182.6 1106.74   206.6 1095.85
   242.6 1078.26   266.7 1067.82   278.7 1063.62   302.7  1057.3   314.7 1055.81
   350.8 1055.44   462.9 1047.14   492.9 1043.39     495 1043.07   507.9 1043.59
   530.7 1048.69   578.2 1057.12   613.8 1058.82   661.3 1066.91   732.6 1076.06
     792 1085.83   851.4 1099.05   922.7 1118.99   946.4 1124.17  1004.2 1134.48
#Mann= 3 , 0 , 0
       0      .1       0   492.9    .045       0   507.9      .1       0
Bank Sta=492.9,507.9
XS Rating Curve= 0 ,0
Exp/Cntr=0.3,0.1

Type RM Length L Ch R = 1 ,17424.3 ,440.625,441.367,440.172
XS GIS Cut Line= 3
     1730451.468      255375.798      1730947.89      255468.342
      1731435.39      255584.822
#Sta/Elev= 30
       0 1110.24    22.6 1105.04    49.7  1101.1    90.4 1092.63   101.9 1089.49
   110.8 1088.42   130.1 1084.68   161.3 1082.39   179.6 1081.83   203.8 1084.61
   215.9 1083.16   288.3 1065.28   336.6 1055.78   372.9  1051.4   469.5  1043.4
   497.5 1040.04     505 1039.48   512.5  1039.7   556.9 1042.82   652.2 1050.76
   676.6  1053.9     701  1055.9   713.2 1060.61   725.4 1070.35   737.6 1075.16
   775.2 1078.32   847.5 1086.22     933 1101.46   980.6 1110.95  1006.2 1115.18
#Mann= 3 , 0 , 0
       0      .1       0   497.5    .045       0   512.5      .1       0
Bank Sta=497.5,512.5
XS Rating Curve= 0 ,0
Exp/Cntr=0.3,0.1

Type RM Length L Ch R = 1 ,16982.9 ,440.604,438.684,437.906
XS GIS Cut Line= 3
     1730479.184      255815.191     1730859.396      255897.475
     1731478.989      255999.354
#Sta/Elev= 30
       0 1096.93    30.8 1099.22      43 1098.74    55.1    1096    79.4 1086.97
   103.7 1079.83   135.2 1068.76   152.3 1063.81   176.6 1058.22   195.1 1054.75
   224.5 1050.05   249.5 1044.76   273.8 1042.04   298.1 1040.66   346.7 1040.61
   374.3 1039.67   383.1 1039.49   389.3 1039.78   563.7 1052.11   611.8  1056.9
   623.8 1056.98   647.9 1054.22   671.9 1053.43   759.9 1053.04   833.1 1055.39
     860 1057.22   864.5 1057.17   913.8 1059.95   984.8 1061.89  1016.9 1063.46
#Mann= 3 , 0 , 0
       0      .1       0   374.3    .045       0   389.3      .1       0
Bank Sta=374.3,389.3
XS Rating Curve= 0 ,0
Exp/Cntr=0.3,0.1

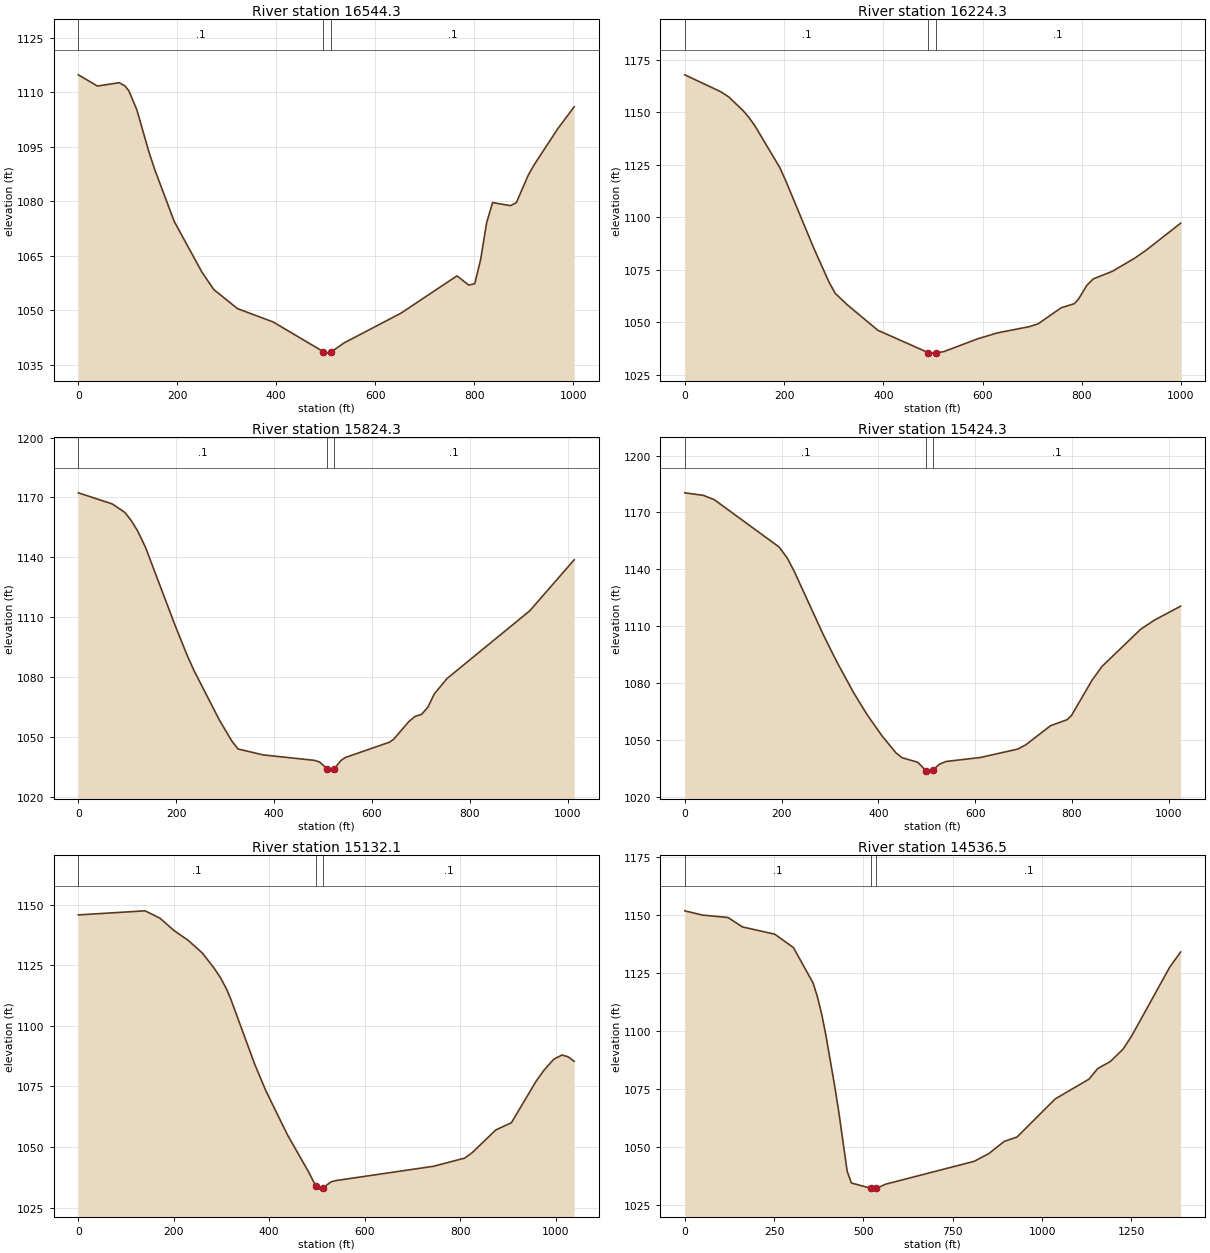
Type RM Length L Ch R = 1 ,16544.3 ,316.509,319.949,325.768
XS GIS Cut Line= 3
      1730249.46      256257.278     1730746.102      256320.689
     1731242.349       256393.14
#Sta/Elev= 30
       0 1114.79    38.7  1111.7    82.4 1112.63    94.4 1111.73   102.4 1110.33
   118.3 1105.14   142.3 1093.75   154.3 1088.76   193.8 1074.43     250 1060.44
   273.9 1055.65   321.8 1050.41   393.6 1046.75   495.3 1038.56   500.7 1038.16
   510.3 1038.43   537.4 1040.99   652.3 1049.18   765.3 1059.43   789.3 1056.89
   801.3 1057.28   813.3 1064.02   825.3 1074.07   837.3 1079.61   873.3 1078.77
   885.3 1079.59   909.3 1087.13   921.3 1090.02   969.3 1099.99  1002.2 1105.98
#Mann= 3 , 0 , 0
       0      .1       0   495.3    .045       0   510.3      .1       0
Bank Sta=495.3,510.3
XS Rating Curve= 0 ,0
Exp/Cntr=0.3,0.1

Type RM Length L Ch R = 1 ,16224.3 ,397.588,400,400.363
XS GIS Cut Line= 3
     1730182.781       256491.14     1730661.177      256628.862
     1731122.684      256825.124
#Sta/Elev= 30
       0 1167.83    72.6 1159.77    88.7 1157.28   117.4 1150.81   129.8  1147.4
   142.1 1143.24   191.5 1123.67   203.9 1117.14   260.3 1085.09   290.4 1069.24
   303.2 1063.77   327.4 1058.33   389.1 1046.17   490.3 1035.57   500.5 1035.29
   505.3  1035.4     522 1036.01   590.8 1042.14   629.5  1044.9     694 1047.88
   712.1 1049.24   758.6 1056.89     785 1058.83   793.6 1061.06   810.2 1067.55
   823.1 1070.63   861.8 1074.26   906.3 1080.45   929.4 1084.23   999.3 1097.15
#Mann= 3 , 0 , 0
       0      .1       0   490.3    .045       0   505.3      .1       0
Bank Sta=490.3,505.3
XS Rating Curve= 0 ,0
Exp/Cntr=0.3,0.1

Type RM Length L Ch R = 1 ,15824.3 ,388.297,400,412.574
XS GIS Cut Line= 3
     1730148.333      256815.995     1730624.813       257012.99
       1731078.7      257217.506
#Sta/Elev= 30
       0 1172.32    69.4 1166.76    95.1 1162.52     108 1158.49   120.8 1153.43
   137.3 1145.04   197.9 1105.88   223.6 1090.27   236.5 1083.31   287.8 1058.78
   313.5 1048.12   326.4 1044.07   377.8 1041.09   482.7 1038.36   493.4 1037.49
   508.1 1034.24   518.8 1032.97   523.1  1034.2     537 1038.33   545.2 1039.75
   635.8 1047.45   644.7 1048.98   675.4 1057.75   688.4 1060.41   701.5  1061.4
   714.5 1064.99   727.5 1071.64   753.5 1079.32   922.8 1113.27  1013.4 1138.78
#Mann= 3 , 0 , 0
       0      .1       0   508.1    .045       0   523.1      .1       0
Bank Sta=508.1,523.1
XS Rating Curve= 0 ,0
Exp/Cntr=0.3,0.1

Type RM Length L Ch R = 1 ,15424.3 ,291.77,292.162,286.595
XS GIS Cut Line= 3
     1730082.097      256906.651     1730391.721      257306.491
     1730683.749      257735.648
#Sta/Elev= 30
       0 1180.36    38.5 1179.03    61.1 1176.72   195.1 1151.78     212  1145.9
   226.3 1138.91   286.3  1105.6   313.6  1091.6   348.7 1075.18   376.4 1063.63
   406.9 1052.54   436.5 1043.34     449  1040.8   481.5 1038.39   498.2 1034.01
   503.9 1033.72   513.2 1034.31   525.7 1037.26     540 1038.81   610.8  1040.9
   687.7 1045.31   704.8 1047.59   756.1 1057.69   790.2  1060.8   799.2 1063.03
   841.6 1081.56   862.5 1088.95   942.1 1108.45   970.9 1113.32  1024.8 1120.63
#Mann= 3 , 0 , 0
       0      .1       0   498.2    .045       0   513.2      .1       0
Bank Sta=498.2,513.2
XS Rating Curve= 0 ,0
Exp/Cntr=0.3,0.1

Type RM Length L Ch R = 1 ,15132.1 ,615.055,595.603,580.075
XS GIS Cut Line= 3
     1729867.585      257067.237     1730170.461      257472.847
     1730557.344       257839.18
#Sta/Elev= 30
       0 1145.83   139.9 1147.51     171 1144.48   200.7 1139.34   230.3 1135.31
   259.9 1130.08     285 1123.71   298.7 1119.65   310.4 1115.25   319.2  1111.2
   369.8 1084.07   393.3 1073.06   438.2 1055.02   482.2 1039.82   497.1 1034.07
   505.5 1032.59   512.1 1033.09     530 1035.63   539.1  1036.1     744 1042.02
   809.4 1045.38   825.7 1047.71   874.8 1057.03   907.5 1060.01   959.1 1077.09
   975.8 1081.71   996.3 1086.23  1013.5 1087.98  1026.2 1087.24    1039 1085.38
#Mann= 3 , 0 , 0
       0      .1       0   497.1    .045       0   512.1      .1       0
Bank Sta=497.1,512.1
XS Rating Curve= 0 ,0
Exp/Cntr=0.3,0.1

Type RM Length L Ch R = 1 ,14536.5 ,581.351,585.364,588.891
XS GIS Cut Line= 3
     1729486.713      257909.295     1730027.565       257956.83
     1730872.169       257976.84
#Sta/Elev= 30
       0 1151.74    49.2 1149.91   120.8 1148.87   161.6  1144.8   251.9 1141.68
     304 1135.93   359.1 1120.66     371 1114.83     383 1107.37   394.9 1098.21
   418.7 1077.05   430.6 1065.64   454.5 1039.57   466.4 1034.54   521.4 1032.25
     526  1031.9   536.4 1032.24   561.7 1034.01   810.1 1043.88   851.1 1047.22
   894.2 1052.47   929.8 1054.32  1036.7 1070.74  1131.7  1079.3  1155.5 1083.79
  1191.1 1086.86  1226.7 1092.18  1250.5 1097.79  1357.4 1127.51  1387.8 1134.02
#Mann= 3 , 0 , 0
       0      .1       0   521.4    .045       0   536.4      .1       0
Bank Sta=521.4,536.4
XS Rating Curve= 0 ,0
Exp/Cntr=0.3,0.1

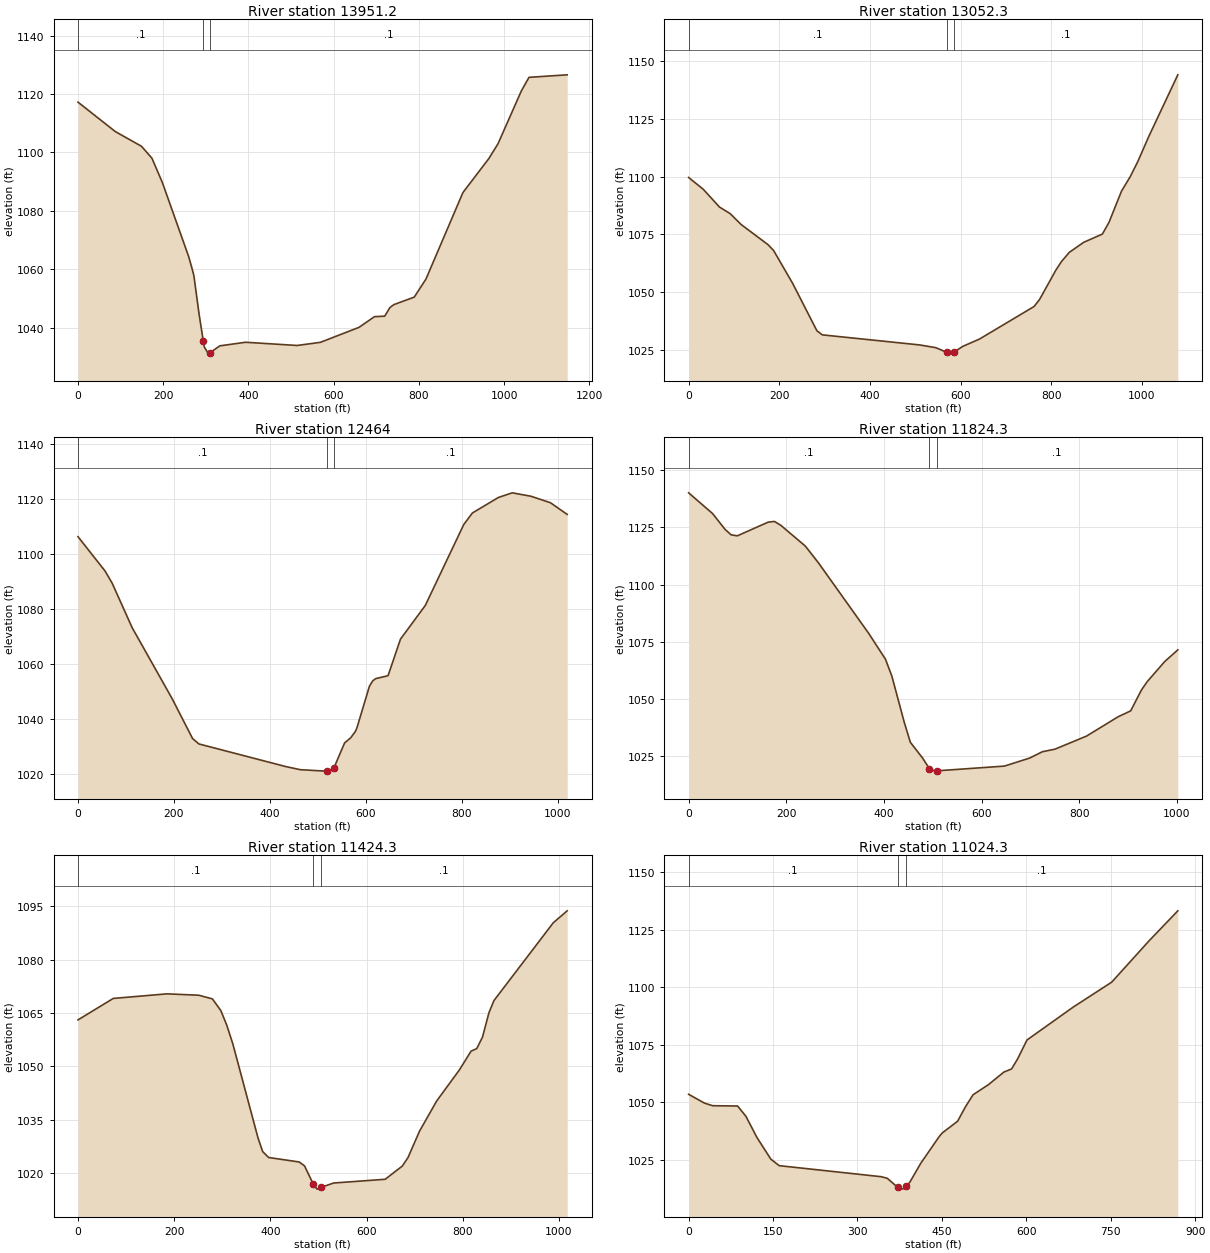
Type RM Length L Ch R = 1 ,13951.2 ,897.48,898.914,898.674
XS GIS Cut Line= 3
     1729593.569      258435.575     1729893.507      258514.788
     1730716.004      258673.076
#Sta/Elev= 30
       0  1117.2    87.6 1107.13     149  1102.1   173.5 1098.01   198.1 1089.64
   259.5 1064.44   266.4 1060.91   271.8 1057.94     284 1044.78   294.1 1035.35
   296.3 1033.44   305.2 1031.32   309.1  1031.4   332.8 1033.81   393.3 1035.04
   514.2 1033.94   568.7 1035.01   659.3 1040.13   695.5 1043.79   719.7 1043.97
   731.8 1046.89     741 1047.91   788.9 1050.48   816.4 1056.64   903.2 1086.27
   964.1 1097.92   985.7 1103.02  1040.2 1121.02  1058.2 1125.69  1147.8 1126.55
#Mann= 3 , 0 , 0
       0      .1       0   294.1    .045       0   309.1      .1       0
Bank Sta=294.1,309.1
XS Rating Curve= 0 ,0
Exp/Cntr=0.3,0.1

Type RM Length L Ch R = 1 ,13052.3 ,578.749,588.286,593.738
XS GIS Cut Line= 3
     1729432.466      259156.952     1730005.882      259217.822
     1730501.131      259305.013
#Sta/Elev= 30
       0 1099.66    32.2 1094.58    68.1 1086.86    91.9 1083.98   115.8 1079.31
   175.2 1070.58   187.5 1068.05   229.3 1053.91     283 1033.34   294.9 1031.54
   509.7 1027.18   545.6 1025.99   569.9 1023.94   581.5 1023.63   584.9    1024
   605.4 1026.59   641.8 1029.72   762.3 1043.81   774.4 1046.85   810.4 1059.56
   822.6 1063.22     840 1067.25   871.9 1071.61   913.1 1075.17   927.8 1080.31
   955.2 1093.74   974.4 1099.99   991.4 1106.63  1015.4  1117.4  1079.5  1144.1
#Mann= 3 , 0 , 0
       0      .1       0   569.9    .045       0   584.9      .1       0
Bank Sta=569.9,584.9
XS Rating Curve= 0 ,0
Exp/Cntr=0.3,0.1

Type RM Length L Ch R = 1 ,12464   ,643.449,639.67,639.638
XS GIS Cut Line= 3
     1729403.887       259501.29     1729849.158      259773.261
     1730305.625      259970.937
#Sta/Elev= 30
       0 1106.22    56.4 1093.72    71.1 1089.34   112.8 1073.13   196.3 1047.24
   238.7 1032.79   251.9 1030.82   432.8 1022.59   463.3 1021.45   516.2 1020.93
   518.3 1021.02   529.6 1021.22   533.3 1022.13   555.4 1031.17   568.4 1033.11
     578 1035.39   581.3 1036.76   607.2 1051.82   614.1 1053.78   620.1 1054.57
     646 1055.65   671.9 1068.95   723.6  1081.2   803.7 1110.63   821.7 1114.83
   875.9 1120.48   904.8 1122.17   943.6 1120.93   984.2 1118.58  1019.2 1114.32
#Mann= 3 , 0 , 0
       0      .1       0   518.3    .045       0   533.3      .1       0
Bank Sta=518.3,533.3
XS Rating Curve= 0 ,0
Exp/Cntr=0.3,0.1

Type RM Length L Ch R = 1 ,11824.3 ,401.199,400,392.319
XS GIS Cut Line= 3
     1728991.099      260021.053     1729460.511      260194.288
     1729921.265      260391.803
#Sta/Elev= 30
       0 1140.18      49 1131.11    74.4 1124.22      87 1121.78    99.7 1121.34
   162.9 1127.34   175.6 1127.65   188.3 1126.03   238.9 1116.87   265.8 1109.52
   368.7 1078.63     403 1067.32   416.1 1059.93   441.4 1039.78     454 1030.92
   479.3 1023.94   492.9 1019.37   504.7 1018.28   507.9  1018.4   646.8 1020.49
   698.5 1024.02   724.3 1026.77   750.2  1027.9   814.8 1033.63   879.3 1042.07
   905.2 1044.68     927 1053.74   938.9 1057.44     975 1066.31  1001.7 1071.39
#Mann= 3 , 0 , 0
       0      .1       0   492.9    .045       0   507.9      .1       0
Bank Sta=492.9,507.9
XS Rating Curve= 0 ,0
Exp/Cntr=0.3,0.1

Type RM Length L Ch R = 1 ,11424.3 ,391.811,400,410.907
XS GIS Cut Line= 3
      1728860.25      260427.007     1729334.978      260574.003
     1729854.308      260609.328
#Sta/Elev= 30
       0 1063.07    73.3 1069.11   185.1  1070.4   251.1 1070.01   279.5 1068.98
     297 1065.69   309.4 1061.55   321.9 1056.34   374.4  1029.8     384 1026.01
   396.4 1024.35   459.9 1023.09     471 1021.99   489.5 1016.79     497 1015.45
   504.5 1015.91   531.6 1017.17   638.7 1018.22   674.4 1021.95   686.3 1024.38
   710.1 1031.76   745.8 1040.26   793.4 1049.07   817.2 1054.26   829.1    1055
     841 1058.22   854.5 1065.11   864.8  1068.5   988.2  1090.4  1017.1 1093.76
#Mann= 3 , 0 , 0
       0      .1       0   489.5    .045       0   504.5      .1       0
Bank Sta=489.5,504.5
XS Rating Curve= 0 ,0
Exp/Cntr=0.3,0.1

Type RM Length L Ch R = 1 ,11024.3 ,393.341,400,410.155
XS GIS Cut Line= 3
     1729050.245      260690.206     1729354.906      260915.583
     1729780.081      261159.701
#Sta/Elev= 30
       0 1053.47    27.8 1049.68    42.7 1048.51      87 1048.38   101.8 1043.92
   121.3 1034.74   146.1  1025.3   160.9 1022.48     342 1017.69   352.9 1017.01
   371.5 1013.06   375.9 1012.29   382.2 1012.47   386.5 1013.51   393.2 1015.36
   412.5 1023.53   445.4 1035.17   450.6 1036.68     478 1041.79   491.7 1047.97
   505.4 1053.27   532.8 1057.67   560.1 1063.12   573.8 1064.48   584.6 1068.87
   601.2 1077.05   683.3 1091.33   751.8 1102.18   817.9 1120.05   869.2 1133.14
#Mann= 3 , 0 , 0
       0      .1       0   371.5    .045       0   386.5      .1       0
Bank Sta=371.5,386.5
XS Rating Curve= 0 ,0
Exp/Cntr=0.3,0.1

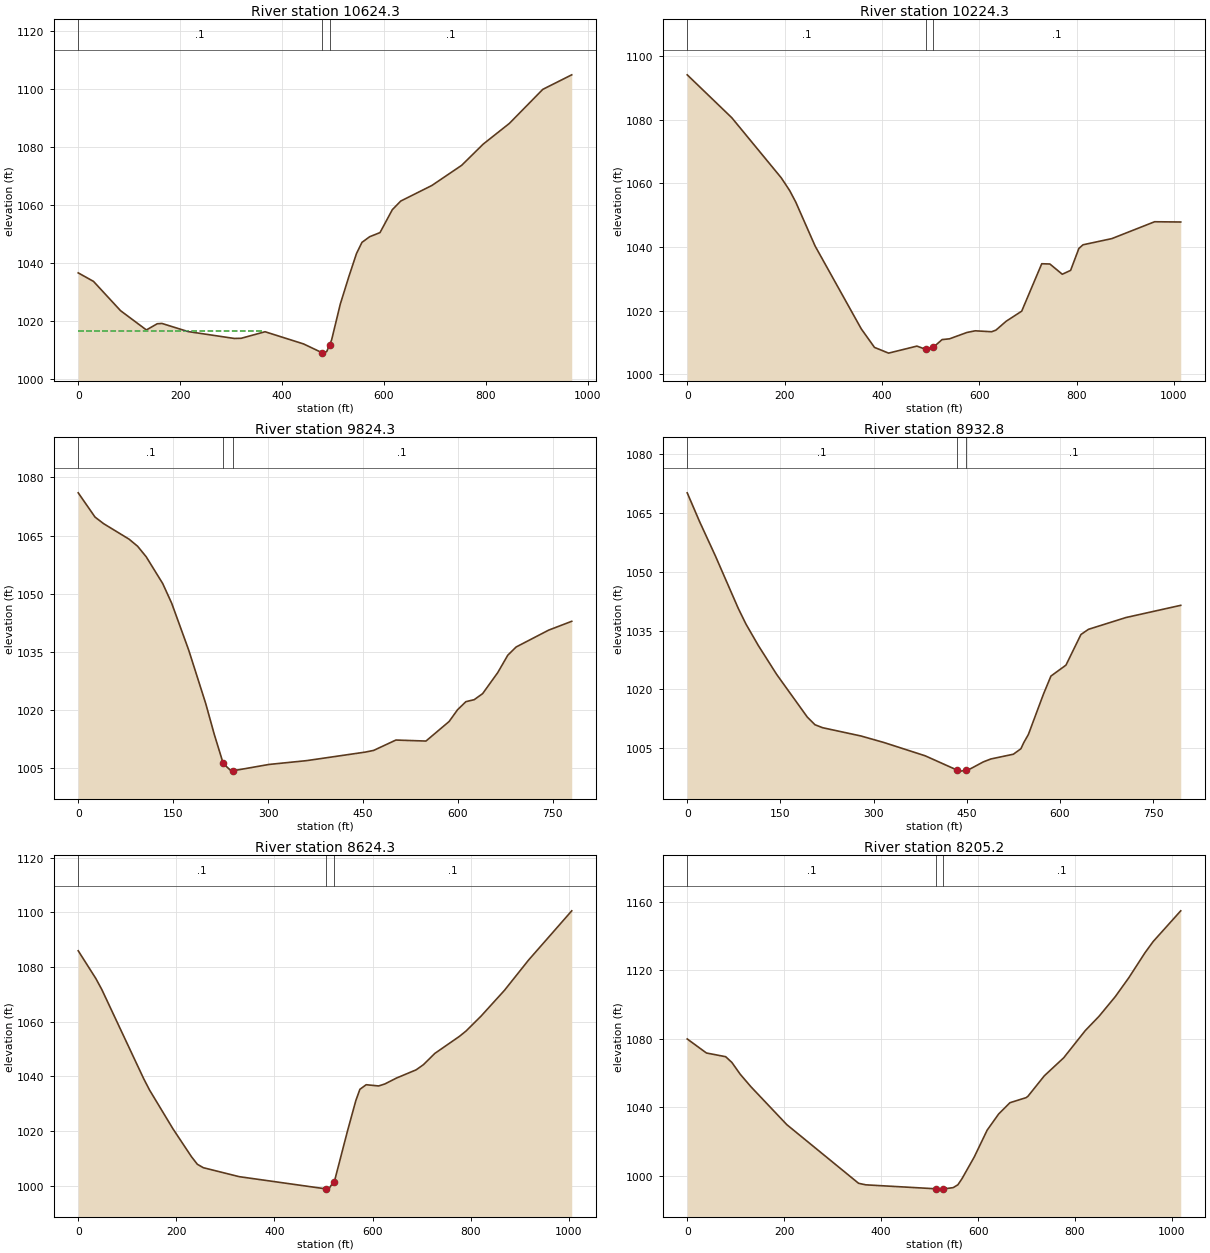
Type RM Length L Ch R = 1 ,10624.3 ,396.644,400,400.177
XS GIS Cut Line= 3
      1728935.45       260905.41     1729236.339      261287.354
     1729518.105      261678.885
#Sta/Elev= 30
       0 1036.66      30 1033.73    83.1 1023.63   133.8 1016.99   155.1 1019.12
   164.3 1019.23   215.6 1016.43   306.3 1014.06   319.8 1014.11   366.7 1016.37
   442.3 1012.17   478.7 1009.13   480.4    1009   487.6 1009.51   493.7 1011.88
   497.4  1013.6   514.4 1025.92   531.3 1035.44   546.1  1043.3   556.9 1047.17
     572 1049.12   592.3 1050.54   616.5 1058.44     633 1061.41     694 1066.77
   752.6 1073.73   794.8 1081.03   846.2 1088.17   911.8 1099.91   968.6 1104.92
#Mann= 3 , 0 , 0
       0      .1       0   478.7    .045       0   493.7      .1       0
#XS Ineff= 2 , 0
          362.14 1016.46
Permanent Ineff=
       F       F
Bank Sta=478.7,493.7
XS Rating Curve= 0 ,0
Exp/Cntr=0.3,0.1

Type RM Length L Ch R = 1 ,10224.3 ,412.711,400,388.784
XS GIS Cut Line= 3
     1728624.091      260999.227     1728868.428      261432.803
     1729166.233      261854.756
#Sta/Elev= 30
       0 1094.16    91.6 1080.66   193.1 1061.78   210.5 1057.76     223 1054.13
   262.8  1040.3   357.6 1014.25   384.8 1008.41   413.8 1006.61     472 1008.82
   490.2 1007.79   495.5 1007.54   505.2 1008.39   523.7 1010.87     539 1011.11
   574.8 1013.11   591.8 1013.63   625.5 1013.34   634.4 1013.85   655.3 1016.63
   687.3 1019.81   728.5 1034.73   745.2 1034.65   770.7 1031.43   787.8 1032.64
   804.8 1039.54   813.3 1040.69   872.6 1042.64   960.4 1047.94  1014.1 1047.86
#Mann= 3 , 0 , 0
       0      .1       0   490.2    .045       0   505.2      .1       0
Bank Sta=490.2,505.2
XS Rating Curve= 0 ,0
Exp/Cntr=0.3,0.1

Type RM Length L Ch R = 1 ,9824.3  ,909.342,891.512,876.086
XS GIS Cut Line= 3
     1728396.304      261581.648     1728604.981      261693.356
      1729092.39      261933.986
#Sta/Elev= 30
       0 1076.02    26.6 1069.76      40 1068.08    80.4 1064.06    93.9 1062.23
   107.4 1059.53   133.5 1052.63   147.8 1047.51   174.7 1035.41   201.6 1021.61
   215.1 1013.66   229.2 1006.18     242 1004.21   244.2 1004.29   301.4 1005.93
   361.1 1006.92   453.8 1009.12     467 1009.56   502.1 1012.23   549.6 1011.97
   586.2 1017.01   599.5 1020.04   612.7 1022.13   625.9 1022.65   639.2 1024.21
   663.1 1029.64   678.9 1034.11   692.1 1036.24   743.5 1040.59     780 1042.87
#Mann= 3 , 0 , 0
       0      .1       0   229.2    .045       0   244.2      .1       0
Bank Sta=229.2,244.2
XS Rating Curve= 0 ,0
Exp/Cntr=0.3,0.1

Type RM Length L Ch R = 1 ,8932.8  ,297.133,308.488,321.544
XS GIS Cut Line= 3
     1728305.208      262609.734     1728734.662      262486.103
     1729076.272      262421.035
#Sta/Elev= 30
       0 1070.12    20.3 1062.64    45.1 1054.12    82.1 1040.68    94.5 1036.67
   114.5 1031.18   143.9 1023.84   193.3 1012.94   205.7 1010.98     218 1010.22
   279.8 1008.11   316.9 1006.44   383.1 1003.06   433.6  999.48   440.6  999.15
   448.6  999.35   452.6  999.46   476.8 1001.51   488.9 1002.25   525.1 1003.46
   537.2 1004.85   541.8  1006.4   549.3  1008.5   573.5 1018.76   585.6 1023.39
   609.8 1026.18   633.9 1033.99     646 1035.31   706.4 1038.32   794.6 1041.43
#Mann= 3 , 0 , 0
       0      .1       0   433.6    .045       0   448.6      .1       0
Bank Sta=433.6,448.6
XS Rating Curve= 0 ,0
Exp/Cntr=0.3,0.1

Type RM Length L Ch R = 1 ,8624.3  ,409.655,419.088,427.908
XS GIS Cut Line= 3
     1728230.379      262671.549     1728730.616      262784.927
     1729190.551      262962.751
#Sta/Elev= 30
       0 1085.89    35.9 1075.75    48.1 1071.72   133.3 1039.16   145.5 1034.92
   193.1 1020.77   230.7  1010.6   242.9 1007.78     255 1006.54   328.1 1003.26
   505.4  998.78   510.7   998.7   520.4 1001.42   523.3 1002.24   548.8 1019.89
   565.9 1031.08   574.2 1035.21     587 1036.89   612.4 1036.44   625.1 1037.17
   648.5 1039.31   688.8 1042.33   703.6 1044.21     727 1048.35   777.1 1054.58
   790.6 1056.54   821.3 1062.01   868.9 1071.42   917.9 1082.46    1006  1100.5
#Mann= 3 , 0 , 0
       0      .1       0   505.4    .045       0   520.4      .1       0
Bank Sta=505.4,520.4
XS Rating Curve= 0 ,0
Exp/Cntr=0.3,0.1

Type RM Length L Ch R = 1 ,8205.2  ,371.662,380.912,386.569
XS GIS Cut Line= 3
     1728148.225      262855.764     1728568.736      263169.325
     1728919.269      263516.742
#Sta/Elev= 30
       0 1079.88    39.6 1071.68    79.3 1069.51    92.1 1066.16   109.1 1059.35
   131.3    1052   205.4 1029.83   353.5  995.55   368.3  994.66   513.1  992.34
   524.5  992.15   528.1  992.25   548.8  993.03   558.4   994.7   566.8  998.23
     592 1010.86   618.7 1026.58   642.3 1035.98   665.8 1042.64   699.2  1045.6
     703 1046.43   736.7 1058.35   776.7 1068.89   821.1 1084.75   849.7 1093.17
   883.1 1104.62     911 1115.64   944.6 1130.34   961.4 1136.85  1018.1 1154.73
#Mann= 3 , 0 , 0
       0      .1       0   513.1    .045       0   528.1      .1       0
Bank Sta=513.1,528.1
XS Rating Curve= 0 ,0
Exp/Cntr=0.3,0.1