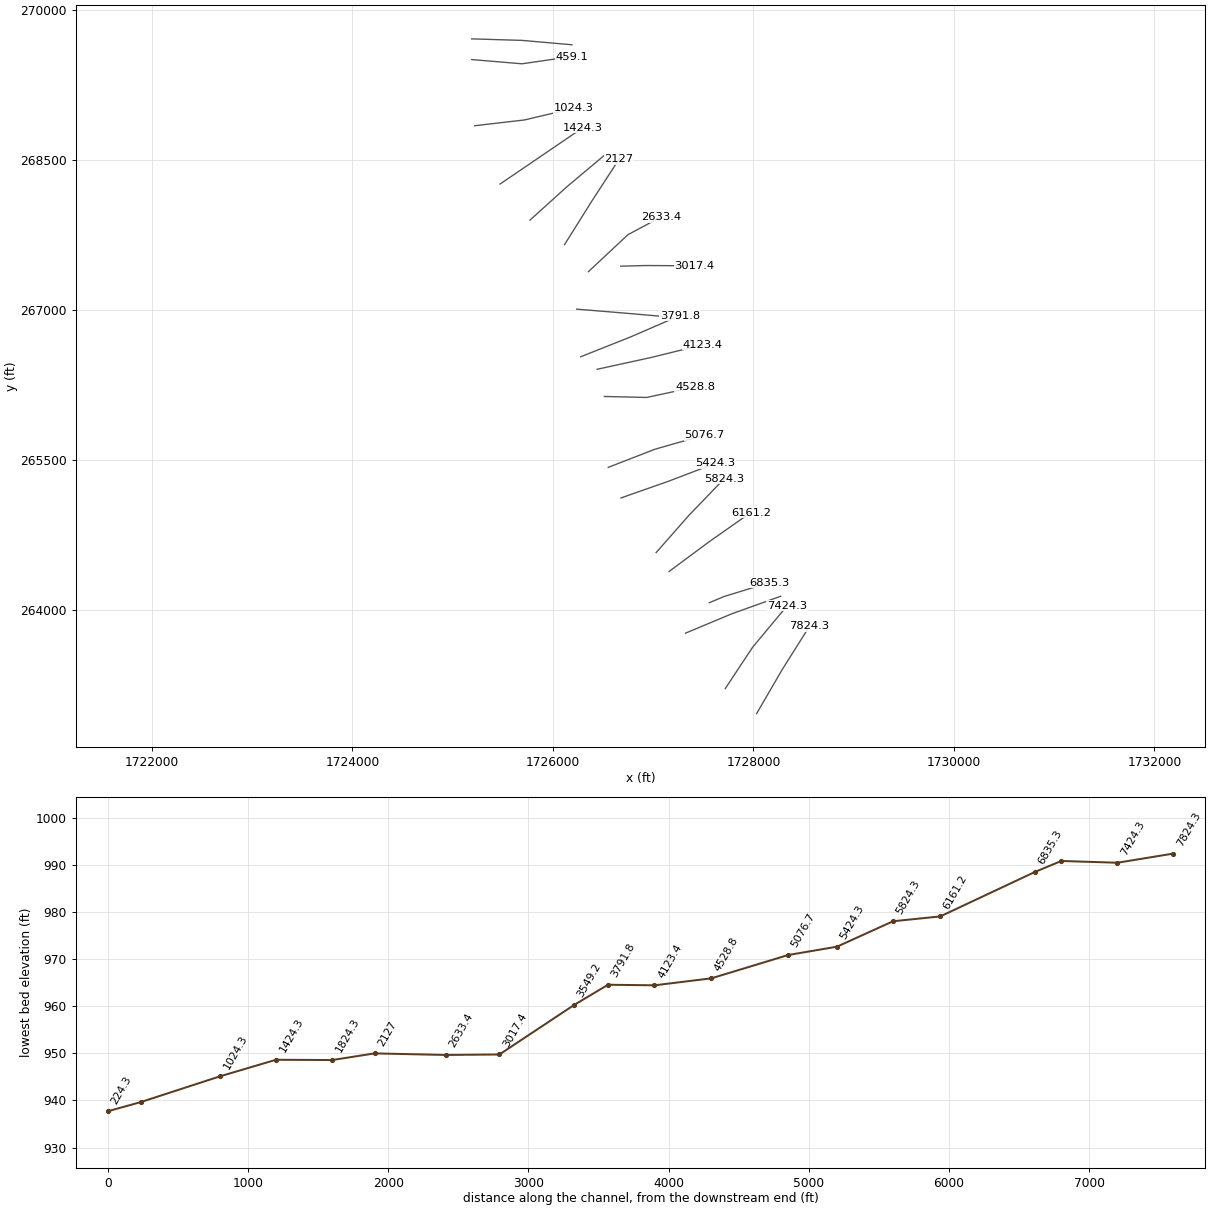
HEC-RAS study BrownsCr.prj: BrownsCr

--- BrownsCr.g01 (geometry) --- (continued)

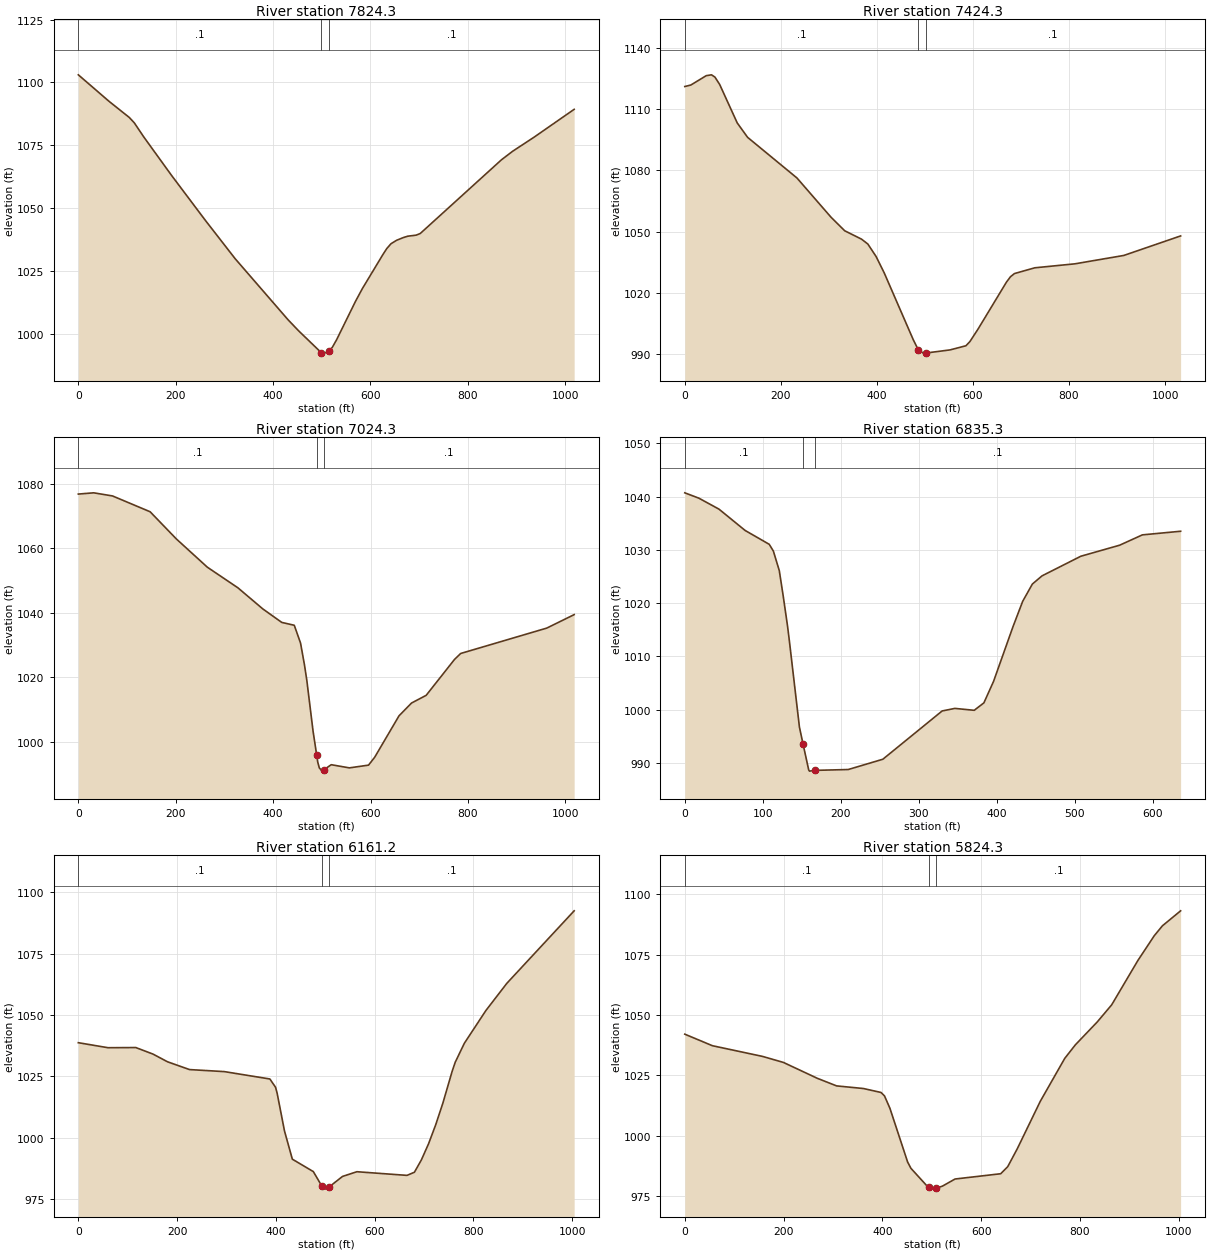
Type RM Length L Ch R = 1 ,7824.3  ,401.705,400,396.707
XS GIS Cut Line= 3
     1728031.722      262969.854     1728286.157      263408.263
     1728558.984      263841.542
#Sta/Elev= 30
       0 1103.04    63.4 1092.45   104.8 1086.07   115.1 1083.91   134.4 1078.35
   191.6 1063.02   261.1 1045.13   321.9 1029.98   430.8 1005.65   452.2 1001.31
   499.4   992.5   504.3  992.39   512.5  992.88   514.4  993.26   521.6  994.67
   530.2   997.6   569.4 1013.02   583.4 1018.05   625.5 1031.56   633.5 1033.95
   642.1 1035.87   653.6 1037.24   667.6 1038.34   676.6 1038.88   693.8 1039.29
   702.4 1039.97     869 1069.24   892.1 1072.66   935.8 1078.21  1018.4 1089.32
#Mann= 3 , 0 , 0
       0      .1       0   499.4    .045       0   514.4      .1       0
Bank Sta=499.4,514.4
XS Rating Curve= 0 ,0
Exp/Cntr=0.3,0.1

Type RM Length L Ch R = 1 ,7424.3  ,413.437,400,387.889
XS GIS Cut Line= 3
     1727718.435      263218.879     1727990.542      263630.939
       1728334.8      264045.006
#Sta/Elev= 30
       0 1121.16    12.6  1121.9    44.6 1126.48    55.5  1126.9    62.7  1125.8
    72.6 1122.18   109.2  1103.3   130.8 1096.24   233.4 1076.35   304.6 1057.04
     333 1050.42   367.8 1046.35   381.1 1043.94   398.3 1037.81   415.4 1029.68
   475.5   997.1   486.3  991.97   496.6  990.44   501.3  990.47   552.3  992.02
   585.3  994.05   593.7  996.14   610.6 1002.26   669.6 1025.22     678 1027.88
   686.4 1029.46   728.6 1032.27   812.3 1034.23   914.1 1038.34  1032.3 1047.91
#Mann= 3 , 0 , 0
       0      .1       0   486.3    .045       0   501.3      .1       0
Bank Sta=486.3,501.3
XS Rating Curve= 0 ,0
Exp/Cntr=0.3,0.1

Type RM Length L Ch R = 1 ,7024.3  ,188.923,188.987,187.922
XS GIS Cut Line= 3
     1727322.126      263772.928     1727780.383      263964.871
     1728270.919      264141.272
#Sta/Elev= 30
       0 1076.77    31.5 1077.16    70.1  1076.2   147.4 1071.29   201.3 1062.85
   264.8  1054.1   327.6  1047.7   379.1 1041.11   417.7 1036.96   443.4 1036.07
   456.3 1030.54   464.4 1023.73   469.2 1018.96     482  1003.2   489.3  995.94
   491.6  993.62   494.9   991.8   500.8  990.82   504.3  991.26   519.3  992.81
   556.5  991.83   595.9  992.68   608.5  995.12   658.5 1007.98   684.2 1011.95
   714.2 1014.33   772.5 1025.48   785.1 1027.32   961.8 1035.19  1018.1 1039.37
#Mann= 3 , 0 , 0
       0      .1       0   489.3    .045       0   504.3      .1       0
Bank Sta=489.3,504.3
XS Rating Curve= 0 ,0
Exp/Cntr=0.3,0.1

Type RM Length L Ch R = 1 ,6835.3  ,669.613,674.08,679.282
XS GIS Cut Line= 3
     1727560.171      264077.034     1727706.576      264138.849
     1728162.057      264278.747
#Sta/Elev= 30
       0 1040.69      18 1039.69    43.8 1037.63    77.3 1033.63   108.2 1031.03
   113.5 1029.76   121.1 1026.09     126 1021.44   131.6 1015.76     134 1012.93
   146.9  996.73   151.4  993.65   158.8  988.69   159.8  988.47   166.4  988.61
   209.4  988.77   253.8   990.7   329.8  999.76   346.1 1000.24   370.9  999.88
   383.3 1001.28   395.7 1005.32   420.6 1015.58     433 1020.33   445.4 1023.57
   457.8 1025.11   507.5 1028.79   557.2 1030.86   586.4  1032.8   635.4 1033.48
#Mann= 3 , 0 , 0
       0      .1       0   151.4    .045       0   166.4      .1       0
Bank Sta=151.4,166.4
XS Rating Curve= 0 ,0
Exp/Cntr=0.3,0.1

Type RM Length L Ch R = 1 ,6161.2  ,332.119,336.933,341.259
XS GIS Cut Line= 3
     1727158.538      264389.033     1727558.043      264685.749
     1727972.429      264976.846
#Sta/Elev= 30
       0  1038.7      60 1036.66   116.5 1036.72   151.3 1034.05   180.8 1030.91
   225.2 1027.75   295.7 1026.92   387.9 1023.92   399.5 1020.51   402.7 1018.04
   417.5 1002.75   433.4  991.25   475.9  986.19   492.6  980.47   501.3  979.05
   507.6  979.89     535  984.22   564.1  986.14   665.6  984.65   680.6  985.93
   694.6  990.91   709.2   997.5   723.7 1005.25   738.2 1014.07     757 1027.03
   763.2 1030.71   781.7 1038.46   825.4 1051.82   867.8 1062.89  1004.1 1092.42
#Mann= 3 , 0 , 0
       0      .1       0   492.6    .045       0   507.6      .1       0
Bank Sta=492.6,507.6
XS Rating Curve= 0 ,0
Exp/Cntr=0.3,0.1

Type RM Length L Ch R = 1 ,5824.3  ,411.56,400,390.083
XS GIS Cut Line= 3
     1727029.332      264577.625     1727360.673      264954.224
     1727709.246      265316.164
#Sta/Elev= 30
       0 1042.08    55.9 1037.31   157.6 1032.88   199.7  1030.4   268.3 1023.84
   307.5 1020.69   361.5 1019.62   397.4 1017.98   404.4 1016.57   415.4 1011.44
   451.3   989.2     458  986.61   489.7  979.51   494.1  979.09   505.1  978.02
   509.1  978.32   522.1   979.3   547.3   982.2   639.7  984.38     654  987.32
   673.3   994.7   719.9 1014.32   769.4 1032.06   790.8 1037.64   835.3 1047.14
   864.5 1054.21   917.7 1072.59   950.7 1082.77   967.2 1086.87  1004.1 1093.07
#Mann= 3 , 0 , 0
       0      .1       0   494.1    .045       0   509.1      .1       0
Bank Sta=494.1,509.1
XS Rating Curve= 0 ,0
Exp/Cntr=0.3,0.1

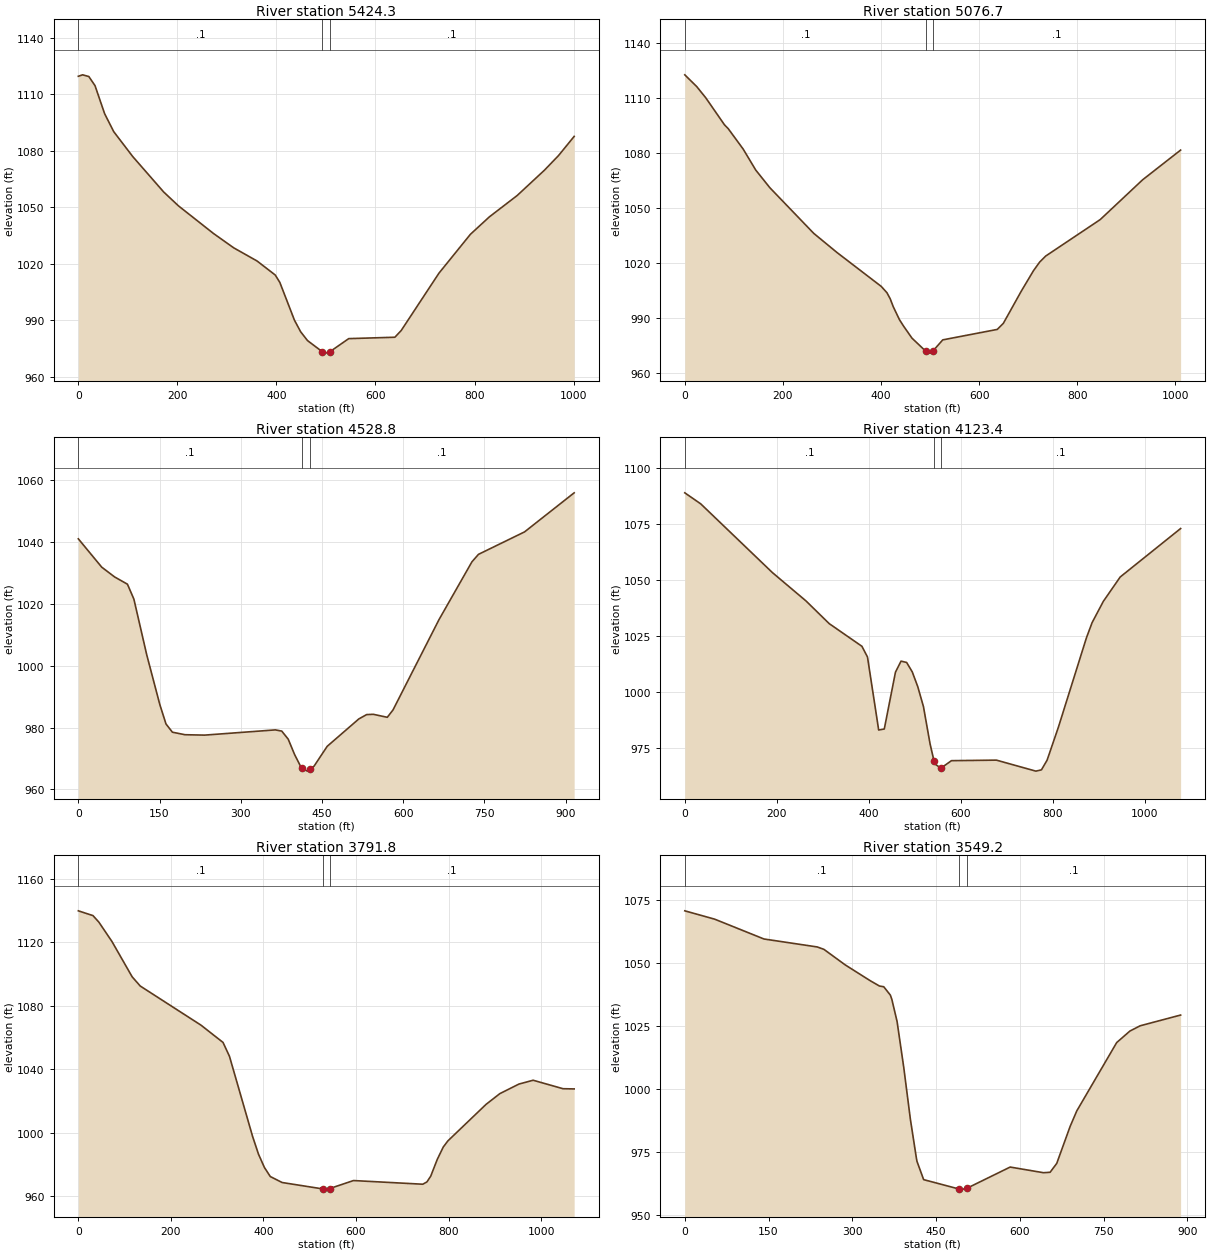
Type RM Length L Ch R = 1 ,5424.3  ,346.848,347.579,345.591
XS GIS Cut Line= 3
     1726678.235      265123.142     1727150.404      265289.021
     1727618.075       265467.95
#Sta/Elev= 30
       0 1119.46     8.6 1120.23    21.2 1119.33    33.7 1114.49    53.1 1099.62
    71.5 1090.08   109.9 1076.87   172.2 1058.13   202.1 1050.75   272.8  1036.1
   313.8 1028.46   360.9 1021.49   397.6 1014.05   406.9 1010.13   436.4   990.1
     449  983.92   462.8  979.27     493   973.3   499.4  972.62     508  973.37
     546  980.31   639.2  981.05   651.9  984.59   728.2 1015.03   791.7 1035.64
   829.9 1044.87   886.2 1056.23   941.4  1069.7   969.7 1077.42  1001.2 1087.57
#Mann= 3 , 0 , 0
       0      .1       0     493    .045       0     508      .1       0
Bank Sta=493,508
XS Rating Curve= 0 ,0
Exp/Cntr=0.3,0.1

Type RM Length L Ch R = 1 ,5076.7  ,556.76,547.956,545.875
XS GIS Cut Line= 3
      1726551.54      265428.564     1727016.847      265609.402
      1727508.72      265750.176
#Sta/Elev= 30
       0 1122.49    24.3 1116.09    42.7 1109.99    80.9 1095.25    88.5 1093.17
   119.1    1082   144.6 1070.62   173.4 1060.98   262.8 1036.13   310.2  1025.7
   400.3 1007.25   412.1 1003.77   418.7  1000.5   424.8  996.25   437.6  989.09
   446.2   985.5   463.1  979.03   491.5  971.83   501.3  970.86   506.5  972.23
   525.9  978.08     637  983.78   649.4  987.09   686.4 1004.83   711.1 1015.88
   723.5 1020.49   735.8 1023.76     847 1043.64   933.3 1065.29  1010.8 1081.49
#Mann= 3 , 0 , 0
       0      .1       0   491.5    .045       0   506.5      .1       0
Bank Sta=491.5,506.5
XS Rating Curve= 0 ,0
Exp/Cntr=0.3,0.1

Type RM Length L Ch R = 1 ,4528.8  ,400.046,405.416,406.616
XS GIS Cut Line= 3
     1726512.564      266136.459     1726935.511      266126.699
      1727417.02      266230.809
#Sta/Elev= 30
       0 1041.01    43.2 1031.85    66.9  1028.7    90.7 1026.34   102.6 1021.52
   126.3 1003.53   150.5  987.43   161.9  981.16   173.7   978.5     197  977.68
   233.2  977.55   363.8  979.24   375.7  978.85   387.6  976.25   399.5  971.24
   412.3  966.83   423.1  965.91   427.3  966.49   435.4  967.53   459.6  973.93
     518  982.78   532.5  984.19   544.7  984.28   570.6  983.31   581.1  985.67
   666.1 1014.89   726.9 1033.57     739 1035.99   824.1 1043.25   915.7 1055.88
#Mann= 3 , 0 , 0
       0      .1       0   412.3    .045       0   427.3      .1       0
Bank Sta=412.3,427.3
XS Rating Curve= 0 ,0
Exp/Cntr=0.3,0.1

Type RM Length L Ch R = 1 ,4123.4  ,327.211,331.573,336.149
XS GIS Cut Line= 3
      1726440.88      266408.007     1726982.215      266526.584
     1727490.953      266651.908
#Sta/Elev= 30
       0 1089.01    34.6 1084.08   190.5 1053.29   263.4 1040.62   313.8 1030.47
     385 1020.31   397.1 1015.51   421.4  982.85   433.6  983.29   457.9 1008.73
     470 1013.67   482.2 1013.07   494.4 1008.86   506.5 1002.15   518.7  993.34
   533.1  976.65   541.6  969.05   543.5  967.65   556.6  965.75   579.6  969.11
   677.4  969.35     763  964.43   775.2     965   787.5  969.36   811.9  984.01
     873 1024.12   885.3 1030.91   909.7 1040.42   946.4 1051.34  1077.7 1073.03
#Mann= 3 , 0 , 0
       0      .1       0   541.6    .045       0   556.6      .1       0
Bank Sta=541.6,556.6
XS Rating Curve= 0 ,0
Exp/Cntr=0.3,0.1

Type RM Length L Ch R = 1 ,3791.8  ,253.077,242.614,231.423
XS GIS Cut Line= 3
     1726277.089      266533.103     1726774.865      266731.321
      1727266.39      266944.319
#Sta/Elev= 30
       0 1139.83    31.6 1136.83    44.3 1132.74    72.5 1120.59   116.3 1098.28
   133.8 1092.46   265.1 1067.82   312.7 1056.94   326.6 1048.22   376.6  997.74
   389.4  986.54   402.2  978.15   414.9  972.46   440.5  968.71   528.5  964.67
   529.9  964.55   543.5  964.94   594.6  969.95   744.4  967.64   753.4   969.1
   761.6  972.75   775.7  983.29   788.7  991.08   798.6  994.92   881.1 1017.93
   910.9 1024.69     952  1030.7   982.8 1033.13  1047.5 1027.79  1071.5 1027.66
#Mann= 3 , 0 , 0
       0      .1       0   528.5    .045       0   543.5      .1       0
#XS Ineff= 2 , 0
                          602.66          969.54
Permanent Ineff=
       F       F
Bank Sta=528.5,543.5
XS Rating Curve= 0 ,0
Exp/Cntr=0.3,0.1

Type RM Length L Ch R = 1 ,3549.2  ,529.227,531.801,533.855
XS GIS Cut Line= 3
     1726236.332      267008.608     1726723.318      266968.286
     1727120.957      266933.551
#Sta/Elev= 30
       0 1070.58    53.4 1067.28   141.8 1059.41   237.1 1056.26     249 1055.32
   287.2 1049.15   332.4 1042.82   348.7 1040.75   356.2 1040.49   368.1 1037.15
   370.7 1035.51   380.1  1026.7     392 1008.59   403.9  987.99   414.7  972.51
   415.8  971.21   427.7     964   490.4  960.32   499.2  960.24   505.4  960.61
   582.6  968.99   642.2  966.75   654.1  966.92     666  970.44   689.9  985.07
   701.8  991.22   773.3 1018.34   797.1 1022.93   815.4    1025   887.8 1029.26
#Mann= 3 , 0 , 0
       0      .1       0   490.4    .045       0   505.4      .1       0
Bank Sta=490.4,505.4
XS Rating Curve= 0 ,0
Exp/Cntr=0.3,0.1

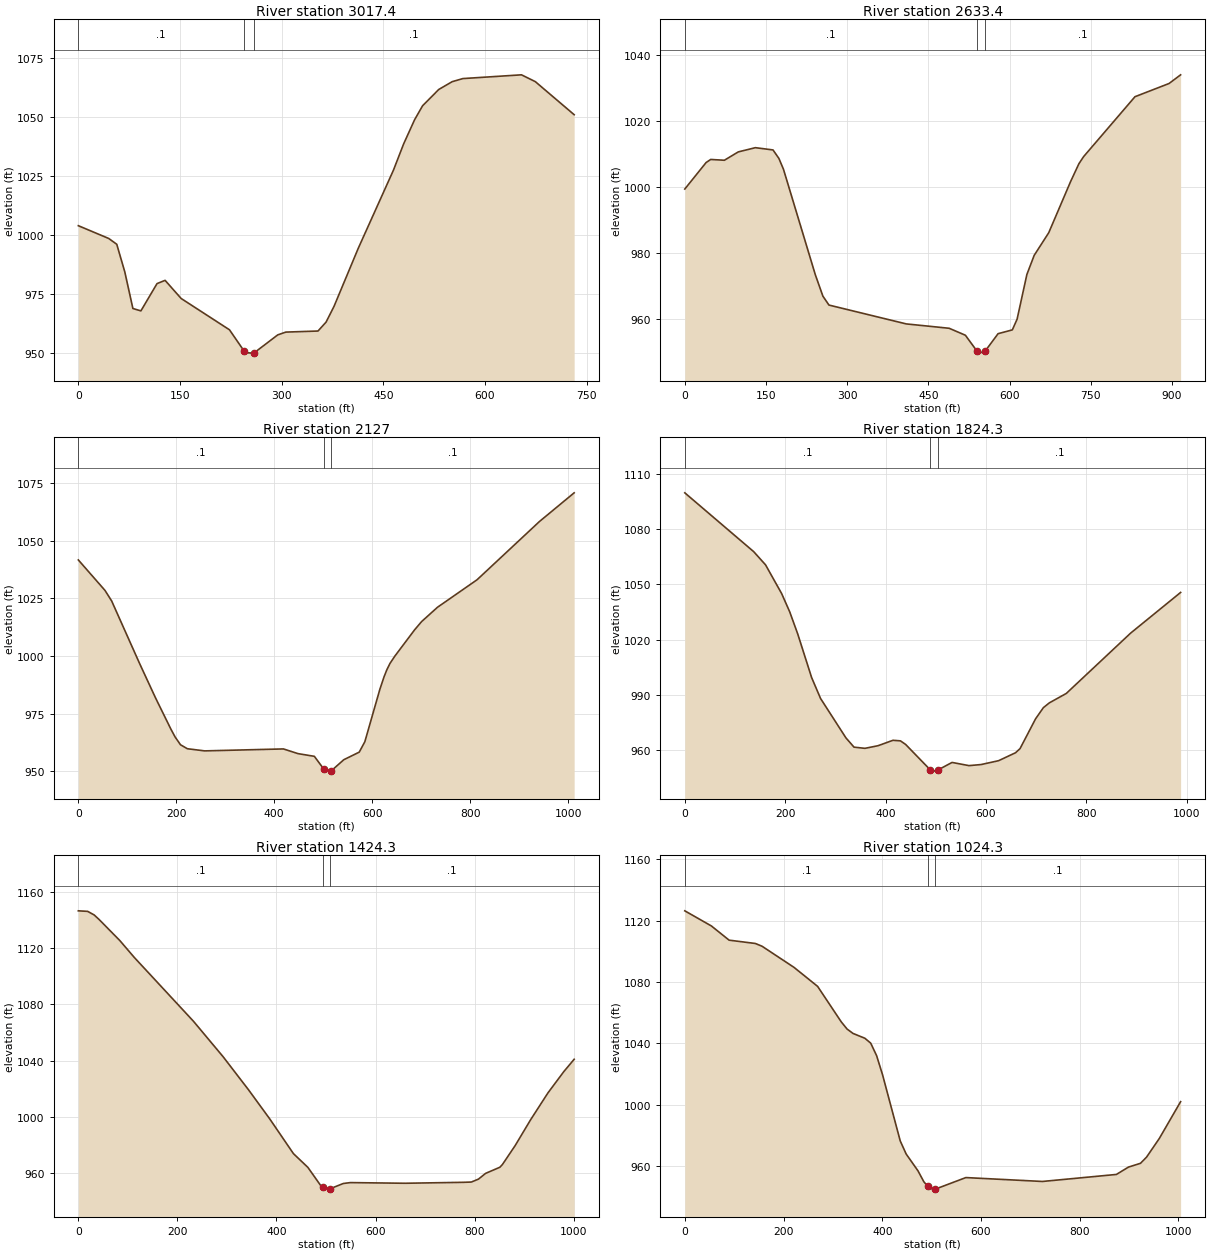
Type RM Length L Ch R = 1 ,3017.4  ,369.006,383.974,395.154
XS GIS Cut Line= 3
      1726677.12      267437.645     1726924.382      267444.152
     1727408.524      267441.441
#Sta/Elev= 30
       0 1003.77    44.8  998.36    56.7  995.89    68.6  984.14    80.5  968.67
    92.3  967.65   116.1  979.22     128   980.6   151.7  972.91     223  959.64
   244.3  950.74   246.7  949.93   258.6  949.75   259.3  949.85   294.2  957.48
   306.1  958.66   353.6  959.12   365.5   962.9   377.3  969.62     413   994.2
   464.9 1027.31   479.9 1038.41   496.1 1048.68   507.9 1054.61   531.7  1061.5
   551.5 1064.81   567.3 1066.13   653.8 1067.72   674.2 1064.83   731.5 1050.82
#Mann= 3 , 0 , 0
       0      .1       0   244.3    .045       0   259.3      .1       0
Bank Sta=244.3,259.3
XS Rating Curve= 0 ,0
Exp/Cntr=0.3,0.1

Type RM Length L Ch R = 1 ,2633.4  ,498.715,506.386,518.102
XS GIS Cut Line= 3
     1726353.687      267382.851     1726748.032      267752.191
     1727079.203      267929.429
#Sta/Elev= 30
       0  999.36    39.5 1007.41    47.9 1008.32    73.1 1008.08    98.8 1010.61
   130.4 1011.89     163  1011.2   173.9 1008.61   182.3 1005.34   241.1  973.41
   255.1  966.91   266.3  964.21   409.1   958.5   488.3  957.18   518.3  955.07
   539.8  950.25   543.6  949.65   554.8  950.25   578.7  955.54     605  956.69
   613.8  959.91   631.9  973.47   645.4  979.27   672.3  986.13   712.7 1001.64
   727.9 1006.99   736.6 1009.16   831.6 1027.33   894.5 1031.33   915.9 1033.96
#Mann= 3 , 0 , 0
       0      .1       0   539.8    .045       0   554.8      .1       0
Bank Sta=539.8,554.8
XS Rating Curve= 0 ,0
Exp/Cntr=0.3,0.1

Type RM Length L Ch R = 1 ,2127    ,308.818,302.701,296.066
XS GIS Cut Line= 3
     1726115.934      267653.479     1726383.467      268081.063
     1726660.529      268507.434
#Sta/Elev= 30
       0 1041.71    54.5 1028.46    68.1 1023.87   124.6  996.96   157.6   981.8
     189  968.22   197.6  964.82   208.6  961.44   222.6  959.71   257.9  958.77
   418.7  959.62   448.6  957.58   481.9  956.41   501.3  950.84   515.5  949.98
   516.3  950.08     542  954.93   573.5  958.22     585  962.74   615.9  985.67
   624.4  991.04   630.1  994.08   636.4  996.78   646.2  999.91   686.7 1011.37
   700.9 1014.93   733.4 1021.16   814.2 1033.11   941.6 1058.41  1012.4 1070.86
#Mann= 3 , 0 , 0
       0      .1       0   501.3    .045       0   516.3      .1       0
Bank Sta=501.3,516.3
XS Rating Curve= 0 ,0
Exp/Cntr=0.3,0.1

Type RM Length L Ch R = 1 ,1824.3  ,403.101,400,397.74
XS GIS Cut Line= 3
     1725771.592      267898.142     1726139.856      268231.583
     1726515.818      268547.255
#Sta/Elev= 30
       0 1099.75   137.3 1067.78   160.9 1060.61   192.9 1045.04   208.9 1035.17
     225 1023.06   252.7  999.36   270.4  988.06   321.1  966.59   337.1   961.6
   358.8  960.95   385.1  962.39   414.7  965.32   429.6  965.01   439.9  963.07
   489.3  949.18   498.7  948.57   504.3  949.22   532.4  953.29   566.1  951.56
   590.2  952.14   625.1  954.24   658.8  958.55   667.8  960.79   698.8     977
   714.3  983.05   726.3  985.67     760  990.78   888.2 1023.56   987.7 1045.64
#Mann= 3 , 0 , 0
       0      .1       0   489.3    .045       0   504.3      .1       0
Bank Sta=489.3,504.3
XS Rating Curve= 0 ,0
Exp/Cntr=0.3,0.1

Type RM Length L Ch R = 1 ,1424.3  ,410.965,400,391.673
XS GIS Cut Line= 3
     1725472.623      268257.948     1725886.211      268539.809
     1726299.798      268821.671
#Sta/Elev= 30
       0 1146.49    18.9  1146.1      32 1143.55    41.8 1140.38    83.9 1125.31
   112.9 1113.38   232.5 1067.95   292.3 1042.76   343.6 1019.25   386.3  998.63
   434.3  973.85   463.4  964.11   488.8  951.43     493  950.27   505.6  948.63
     508  948.86   534.9  952.63   549.2  953.27   659.7   952.8   779.1  953.48
   793.5  953.67   807.8  955.75   822.2  959.82     851  964.18   856.2  966.13
   881.9  979.59   913.3  998.07   948.3 1017.15   980.3 1032.26    1001 1040.95
#Mann= 3 , 0 , 0
       0      .1       0     493    .045       0     508      .1       0
Bank Sta=493,508
XS Rating Curve= 0 ,0
Exp/Cntr=0.3,0.1

Type RM Length L Ch R = 1 ,1024.3  ,569.394,565.223,563.242
XS GIS Cut Line= 3
     1725219.918      268840.153     1725716.339      268897.873
     1726207.428      269014.126
#Sta/Elev= 30
       0 1126.35    53.9 1116.49    89.8 1107.24   142.9 1105.09   156.5 1103.29
   221.3 1089.52   269.1 1077.13   316.9 1054.05   328.8 1049.34   340.8  1046.5
   364.7 1043.38   376.6 1040.19   388.6 1032.01   400.6  1019.6   436.4  976.52
   448.4  967.99   472.3  957.07   484.2  949.93   492.3   946.9   496.2   945.4
   507.3  945.12   507.5  945.11   569.3  952.63   724.5   950.1   874.3  954.67
   898.7  959.46   923.1  961.93   935.3  965.91   961.3  978.13  1004.4 1002.07
#Mann= 3 , 0 , 0
       0      .1       0   492.3    .045       0   507.3      .1       0
Bank Sta=492.3,507.3
XS Rating Curve= 0 ,0
Exp/Cntr=0.3,0.1

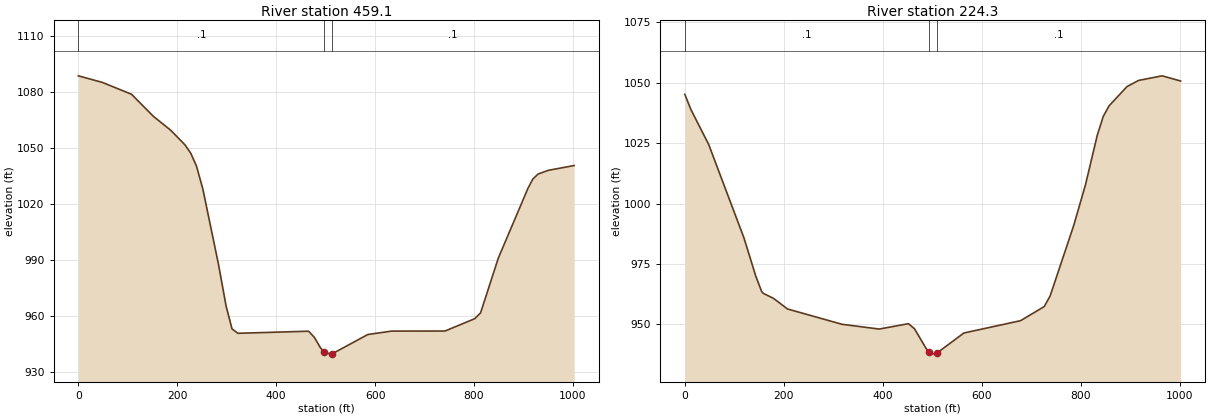
Type RM Length L Ch R = 1 ,459.1   ,233.886,234.777,229.551
XS GIS Cut Line= 3
     1725189.446      269501.002     1725690.475      269458.707
     1726184.998      269530.282
#Sta/Elev= 30
       0 1088.62    48.6 1085.09   107.6 1078.74   151.6 1066.97   186.9 1059.46
   215.4 1051.74   227.3  1047.2   238.9 1040.32   251.9 1027.86   283.4  987.65
   298.8  965.34   310.7  953.16   322.6  950.79   465.6  951.91   477.5  948.52
   489.4  943.09   497.5  940.72   510.4  939.64   512.5   939.7   585.3  950.14
   633.3  951.96   741.3     952   801.3  958.59   813.3  961.74   849.2  991.07
   909.2 1028.46   919.1 1033.41   929.6 1036.06   950.5 1038.05  1002.5  1040.6
#Mann= 3 , 0 , 0
       0      .1       0   497.5    .045       0   512.5      .1       0
Bank Sta=497.5,512.5
XS Rating Curve= 0 ,0
Exp/Cntr=0.3,0.1

Type RM Length L Ch R = 1 ,224.3   ,212.019,224.303,237.877
XS GIS Cut Line= 3
      1725189.53      269707.678     1725690.798      269692.482
     1726189.204      269648.719
#Sta/Elev= 30
       0 1045.19    12.7 1038.77    48.3 1024.47   119.6  985.76   143.4     970
   155.3   963.6   158.6  962.85     179  960.81   207.6  956.38   317.8  950.04
   392.8  948.08   451.9   950.3   464.1  948.19   487.8  939.97     494  938.77
   499.7   937.7     509  938.09   563.9  946.44   678.5  951.55   726.2  957.38
   738.1  961.75   785.8  990.95   809.6 1007.81   833.4 1028.29   845.4 1036.05
   857.3 1040.47   893.5 1048.43   916.9 1050.98   964.5 1052.88  1001.8 1050.74
#Mann= 3 , 0 , 0
       0      .1       0     494    .045       0     509      .1       0
Bank Sta=494,509
XS Rating Curve= 0 ,0
Exp/Cntr=0.3,0.1

Chan Stop Cuts=-1
Use User Specified Reach Order=0